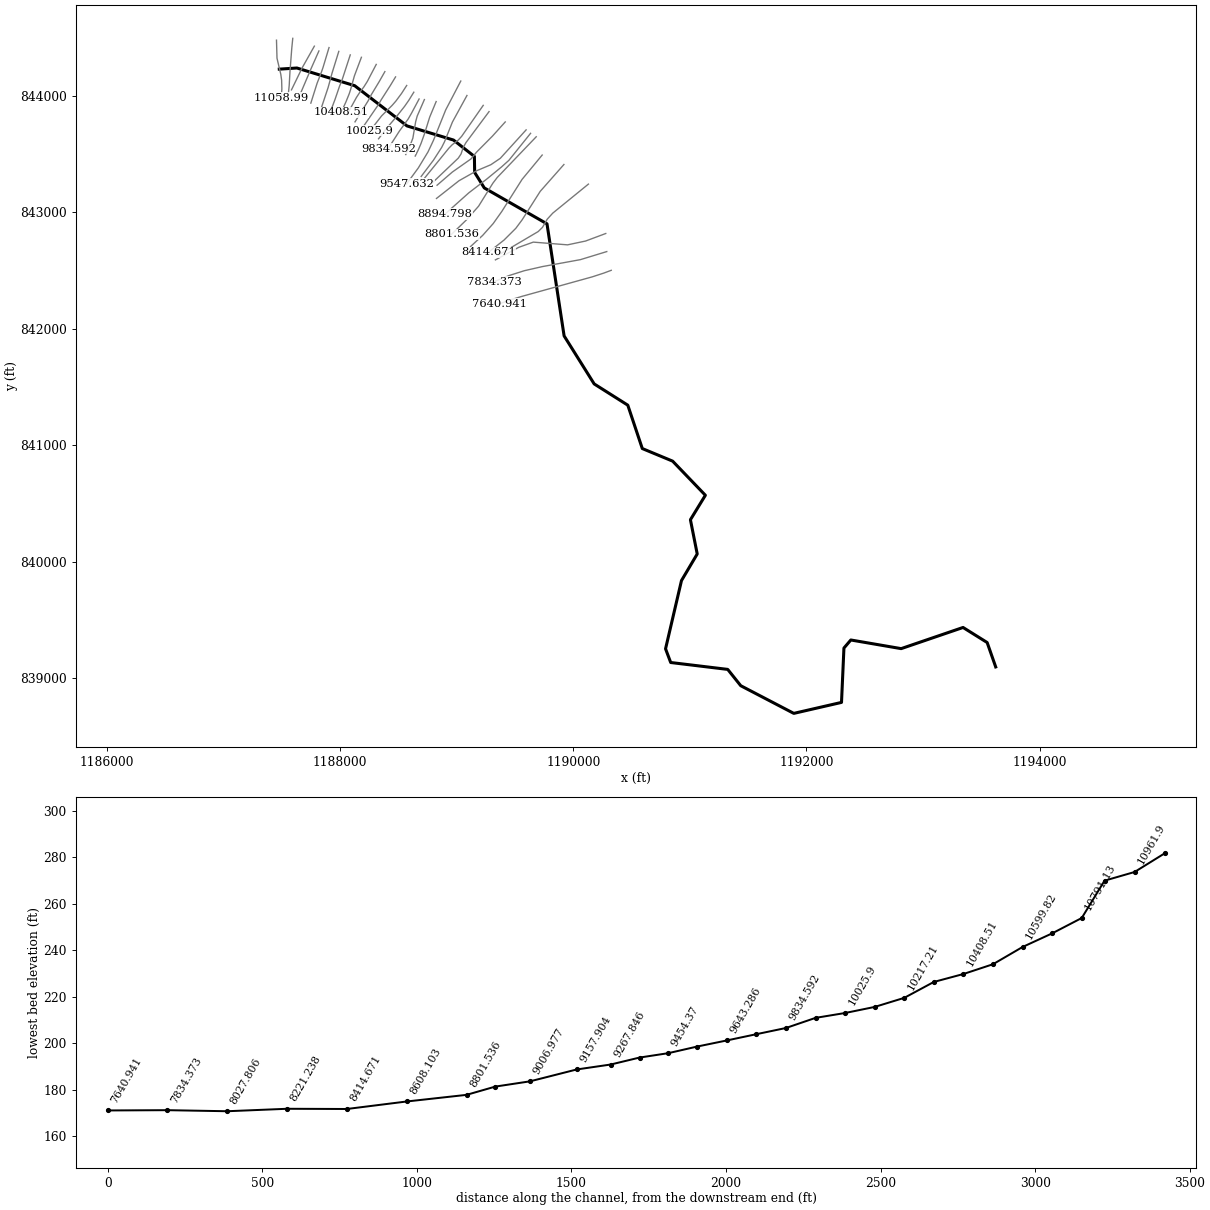
--- 103_ras.prj (project) ---

Proj Title=103
Current Plan=p01
Default Exp/Contr=0.3,0.1
English Units
Geom File=g01
Flow File=f01
Plan File=p01
Y Axis Title=Elevation
X Axis Title(PF)=Main Channel Distance
X Axis Title(XS)=Station
BEGIN DESCRIPTION:
RFD model 103 exported to HEC-RAS
END DESCRIPTION:

--- 103_ras.p01 (plan) ---

Plan Title=Plan 01
Program Version=4.10
Short Identifier=Plan 01
Geom File=g01
Flow File=f01
Subcritical Flow
Calc Critical at every XS
Secant Critical Depth

--- 103_ras.f01 (steady flow) ---

Flow Title=Flow 01
Program Version=5.01
Number of Profiles= 5
Profile Names=10yr,25yr,50yr,100yr,500yr
River Rch & RM=103,47,11058.99
  152.79  273.01  390.09  531.35   954.4
River Rch & RM=103,47,10791.13
   156.5  279.79  399.97   545.1  980.53
River Rch & RM=103,47,10695.47
  168.23  301.23  431.28  588.74 1063.68
River Rch & RM=103,47,10599.82
  176.24   315.9  452.72  618.65 1120.89
River Rch & RM=103,47,10504.17
  212.46  382.39  550.18  755.02 1383.59
River Rch & RM=103,47,10408.51
  220.42  397.03  571.68  785.18 1442.08
River Rch & RM=103,47,10312.86
  226.53  408.29  588.23  808.41 1487.22
River Rch & RM=103,47,10217.21
  232.64  419.55  604.78  831.67 1532.47
River Rch & RM=103,47,10121.55
  252.16  455.55   657.8  906.22 1678.04
River Rch & RM=103,47, 10025.9
  255.21  461.18  666.09  917.89 1700.89
River Rch & RM=103,47,9930.246
  261.91  473.55  684.33  943.58 1751.24
River Rch & RM=103,47,9834.592
     285  516.27  747.38  1032.5 1926.14
River Rch & RM=103,47,9738.939
  288.64  523.01  757.35 1046.56 1953.88
River Rch & RM=103,47,9643.286
  295.32  535.37  775.62 1072.36 2004.83
River Rch & RM=103,47,9547.632
  299.56  543.23  787.24 1088.79 2037.31
River Rch & RM=103,47, 9454.37
   303.2  549.97  797.21 1102.88 2065.19
River Rch & RM=103,47,9361.108
  310.47  563.45  817.16 1131.08 2121.04
River Rch & RM=103,47,9157.904
  459.71  841.52 1230.54 1718.48 3300.32
River Rch & RM=103,47,9006.977
  476.47  872.87 1277.34 1785.29 3436.07
River Rch & RM=103,47,8894.798
  491.41  900.85 1319.14    1845 3557.67
River Rch & RM=103,47,8801.536
   493.2  904.21 1324.16 1852.17 3572.29
River Rch & RM=103,47,8608.103
  561.75 1032.84 1516.67 2127.71  4136.3
River Rch & RM=103,47,8414.671
  568.89 1046.26 1536.78 2156.54 4195.55
River Rch & RM=103,47,8221.238
  570.08 1048.49 1540.13 2161.34 4205.43
River Rch & RM=103,47,8027.806
  576.03 1059.67 1556.89 2185.38 4254.87
River Rch & RM=103,47,7834.373
  807.29 1496.13 2213.78 3131.29 6222.82
River Rch & RM=103,47,7640.941
  813.76 1508.39  2232.3 3158.05 6279.06
River Rch & RM=103,47,7447.508
  882.54 1638.79 2429.42 3443.23 6879.89
River Rch & RM=103,47,7279.075
  887.23  1647.7  2442.9 3462.76 6921.15
River Rch & RM=103,47,7134.203
  903.67 1678.89 2490.11 3531.14 7065.69
River Rch & RM=103,47,6797.881
  925.37 1720.11  2552.5 3621.57  7257.1
River Rch & RM=103,47, 6602.52
  937.09 1742.38 2586.24 3670.48 7360.74
River Rch & RM=103,47,6407.159
 1034.82 1928.29 2868.15 4079.74 8230.91
River Rch & RM=103,47,6211.799
 1041.25 1940.53 2886.74 4106.75 8288.51
River Rch & RM=103,47,6016.438
 1045.34 1948.32 2898.56 4123.94 8325.19
River Rch & RM=103,47,5821.078
 1051.18 1959.44 2915.46  4148.5 8377.61
River Rch & RM=103,47,5625.717
 1062.28 1980.58 2947.56 4195.18 8477.28
River Rch & RM=103,47,5430.356
 1066.95 1989.48 2961.08 4214.84 8519.28
Boundary for River Rch & Prof#=103,47,1
Up Type= 0
Dn Type= 2
Boundary for River Rch & Prof#=103,47,2
Up Type= 0
Dn Type= 2
Boundary for River Rch & Prof#=103,47,2
Up Type= 0
Dn Type= 2
Boundary for River Rch & Prof#=103,47,2
Up Type= 0
Dn Type= 2
Boundary for River Rch & Prof#=103,47,2
Up Type= 0
Dn Type= 2

--- 103_ras.g01 (geometry) ---

Geom Title=103
Program Version=4.10

River Reach=103,47
Reach XY= 30
1187478.29436839844230.496970698 1187629.4081125844240.157597587
1188124.93730086844088.3436663151188573.80174264843743.003877774
1188972.44899753843621.7100300941189151.68574533843481.101883635
1189154.00345796 843343.584031091189236.66868016843210.701609448
1189774.37892672842902.4452842031189921.21034959841940.397172838
1190179.20672297841528.0393201261190467.37615061841345.712271452
1190591.76026499840973.3324651421190852.11709532840865.172348917
1191132.84432653840572.367877245 1191004.5110248840362.367942974
1191062.84433246840068.2013615671190927.84436548  839839.8680996
1190791.17772198839254.0349432831190835.34437227839136.534976706
1191324.51089358839077.3683133421191436.17752343838937.368351489
1191891.17738295838699.8684084861192300.34393218838794.035035491
1192321.17727292839260.7015636711192380.34392422839329.868208185
1192812.01046199839255.7015509611193342.84364468 839437.36814858
1193549.51024696 839308.201514111193622.90941665839098.585157782

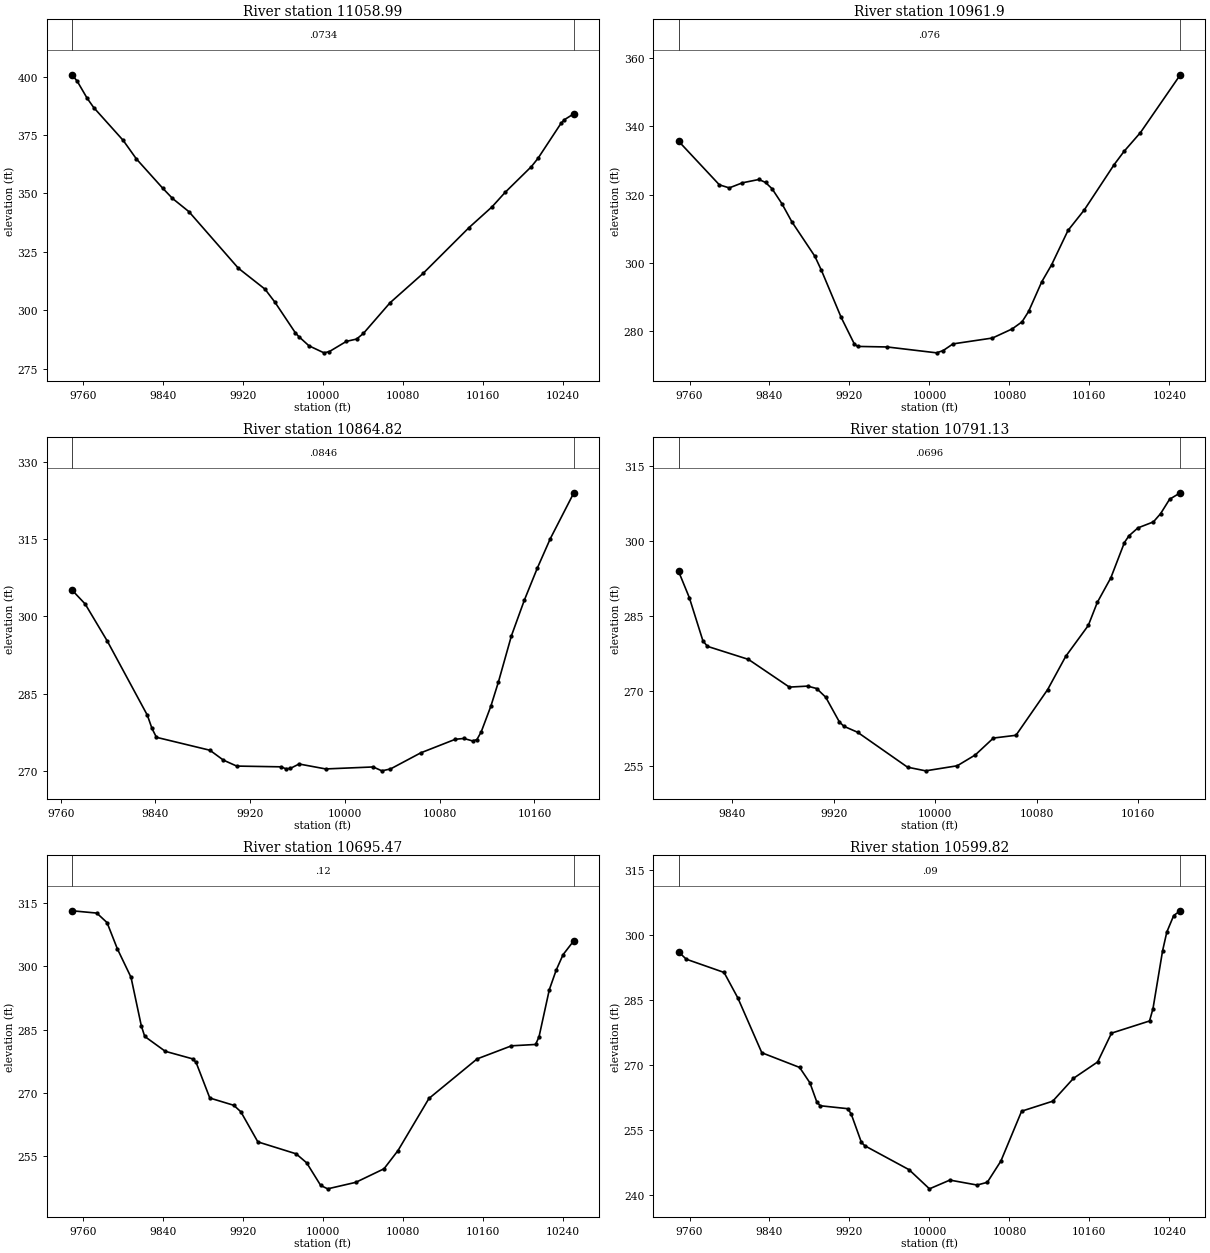
Type RM Length L Ch R = 1 ,11058.99,97.082200,97.082200,97.082200
XS GIS Cut Line= 6
1187454.27498482844479.1768504961187458.69652372844323.846088733
1187491.09111702844186.8136692321187498.31182662844136.377352915
 1187500.4052807844062.7108718741187495.63944425 843982.15811688
#Sta/Elev= 30
9749.078 400.8469754.308398.0343 9764.15390.79719770.712386.8118 9800.24372.7227
9813.364364.82539839.624352.31499849.492347.89189865.938342.21619915.411317.9806
9942.054309.01199952.044303.37929972.344290.34949975.753288.74499985.979284.7631
   10001281.746510006.43282.298510023.42286.660310033.61287.6496 10040.4290.0449
10067.04303.177710100.15315.7766 10146.1 335.41110169.07344.281110182.22 350.504
10208.51361.555210215.08365.088910238.09380.068710241.38381.5901 10250.9384.1523
#Mann= 3 , 0 , 0
9749.078  0.0734       09749.078  0.0734       0 10250.9  0.0734       0
#XS Ineff= 2 , 0
       0                               0
Bank Sta=9749.078,10250.9
Exp/Cntr=0.3,0.1

Type RM Length L Ch R = 1 , 10961.9,97.082300,97.082300,97.082300
XS GIS Cut Line= 6
1187593.91744286844494.9199123221187584.93371969844404.454339109
1187572.86436975844245.8338844651187570.47641452844218.775720682
1187563.32997051 844090.24585501 1187553.4669347 843994.66253186
#Sta/Elev= 30
 9749.01 335.6849789.868322.89659799.759322.00259812.947323.49449829.432324.4638
9836.025323.59599842.614321.73959852.485317.34869862.356312.09219885.388 301.995
9891.969 297.8669911.711284.10349924.872276.33479928.162275.61889957.775275.4581
10007.14273.740310013.72274.405310023.61276.360510063.04278.073910082.76280.7363
10092.62282.808910099.19285.837910112.33294.510710122.19299.492910138.62309.5509
10155.05315.611310184.73 328.78810194.63332.671110211.12338.197510250.98355.0991
#Mann= 3 , 0 , 0
 9749.01   0.076       0 9749.01   0.076       010250.98   0.076       0
#XS Ineff= 2 , 0
       0                               0
Bank Sta=9749.01,10250.98
Exp/Cntr=0.3,0.1

Type RM Length L Ch R = 1 ,10864.82,73.694900,73.694900,73.694900
XS GIS Cut Line= 3
1187779.07788716844427.7870977251187676.04434664844244.495851937
1187582.77187834844052.528097469
#Sta/Elev= 30
9769.578305.12629780.607302.43739799.425295.18089833.181280.80199837.062278.2404
9840.825276.52719885.989274.0131 9897.28272.10629908.571270.93779946.208270.7916
9949.972270.41849953.735270.46859961.263271.34179983.721270.382910023.84270.7683
10031.14270.013110038.44270.378910063.97273.504910093.15276.142310100.44276.3053
10107.74275.821110111.39 276.08110115.03277.577210123.19282.571210129.62287.3184
10140.57296.261110151.51303.201210162.45309.4154 10173.4315.129510193.27324.0343
#Mann= 3 , 0 , 0
9769.578  0.0846       09769.578  0.0846       010193.27  0.0846       0
#XS Ineff= 2 , 0
       0                               0
Bank Sta=9769.578,10193.27
Exp/Cntr=0.3,0.1

Type RM Length L Ch R = 1 ,10791.13,95.653400,95.653400,95.653400
XS GIS Cut Line= 3
1187818.12217623844386.5736815041187747.83373028 844227.88499333
1187660.86045647844023.244880676
#Sta/Elev= 30
9797.519293.88299806.017288.61489816.782279.9451 9820.37278.85539852.665276.2481
9884.959270.70449899.312   270.99906.488 270.4239913.665268.6727 9924.43263.7298
9928.018262.85789938.783261.66849978.207254.67589992.466253.945310017.42254.9586
10031.68257.134110045.94260.505810063.76261.060810088.72270.194510102.98276.8428
 10120.8283.033410127.93287.657110138.63292.589610149.32 299.63210152.88  300.98
10160.01302.567810172.19303.764910177.84305.407510184.97308.299310193.43309.5915
#Mann= 3 , 0 , 0
9797.519  0.0696       09797.519  0.0696       010193.43  0.0696       0
#XS Ineff= 2 , 0
       0                               0
Bank Sta=9797.519,10193.43
Exp/Cntr=0.3,0.1

Type RM Length L Ch R = 1 ,10695.47,95.653400,95.653400,95.653400
XS GIS Cut Line= 6
1187904.85629787844415.5873743341187853.37394808844244.625102928
1187839.93108897844205.7402702021187828.35525987844175.591776539
1187802.42143411844108.6820182961187748.86709337843938.722797725
#Sta/Elev= 30
9749.015313.15599773.725312.61069784.004310.36029794.283304.16819807.989297.4023
9818.268 285.9299821.694283.41089842.252279.88959869.663278.0973 9873.09  277.25
9886.795268.8305 9910.78267.10789917.833265.57669934.859258.44719973.102255.6248
9983.657253.49829997.731248.130410004.73247.331710032.88248.875410061.03 252.076
10075.05256.395810106.01268.729210154.17278.089910188.57281.188910212.65281.5099
10216.09283.297410226.41294.479210233.29299.108810240.17 302.77110250.96306.0764
#Mann= 3 , 0 , 0
9749.015    0.12       09749.015    0.12       010250.96    0.12       0
#XS Ineff= 2 , 0
       0                               0
Bank Sta=9749.015,10250.96
Exp/Cntr=0.3,0.1

Type RM Length L Ch R = 1 ,10599.82,95.653400,95.653400,95.653400
XS GIS Cut Line= 6
1187988.65817306844382.9351714131187930.58368116844195.558323363
1187916.63018493844143.5758015891187916.14511363844141.635516602
1187897.08994198844072.428686173 1187840.7323977843903.380473446
#Sta/Elev= 30
9749.007296.15039756.768294.4491 9794.55291.3942 9808.29 285.5339832.333272.8661
9870.116269.4815 9880.42265.9376 9887.29261.54079890.725260.64259918.203259.9667
9921.638258.80079931.942252.19059935.377251.40619979.646245.884210000.02241.4722
10020.43243.492210047.66242.348410057.87242.975710071.48247.883810092.21259.3856
10123.33261.690610144.08266.965210168.29 270.75110182.12277.391610220.17280.1969
10223.62283.029610233.26296.429310237.46300.707710244.37304.531610250.98305.6211
#Mann= 3 , 0 , 0
9749.007    0.09       09749.007    0.09       010250.98    0.09       0
#XS Ineff= 2 , 0
       0                               0
Bank Sta=9749.007,10250.98
Exp/Cntr=0.3,0.1

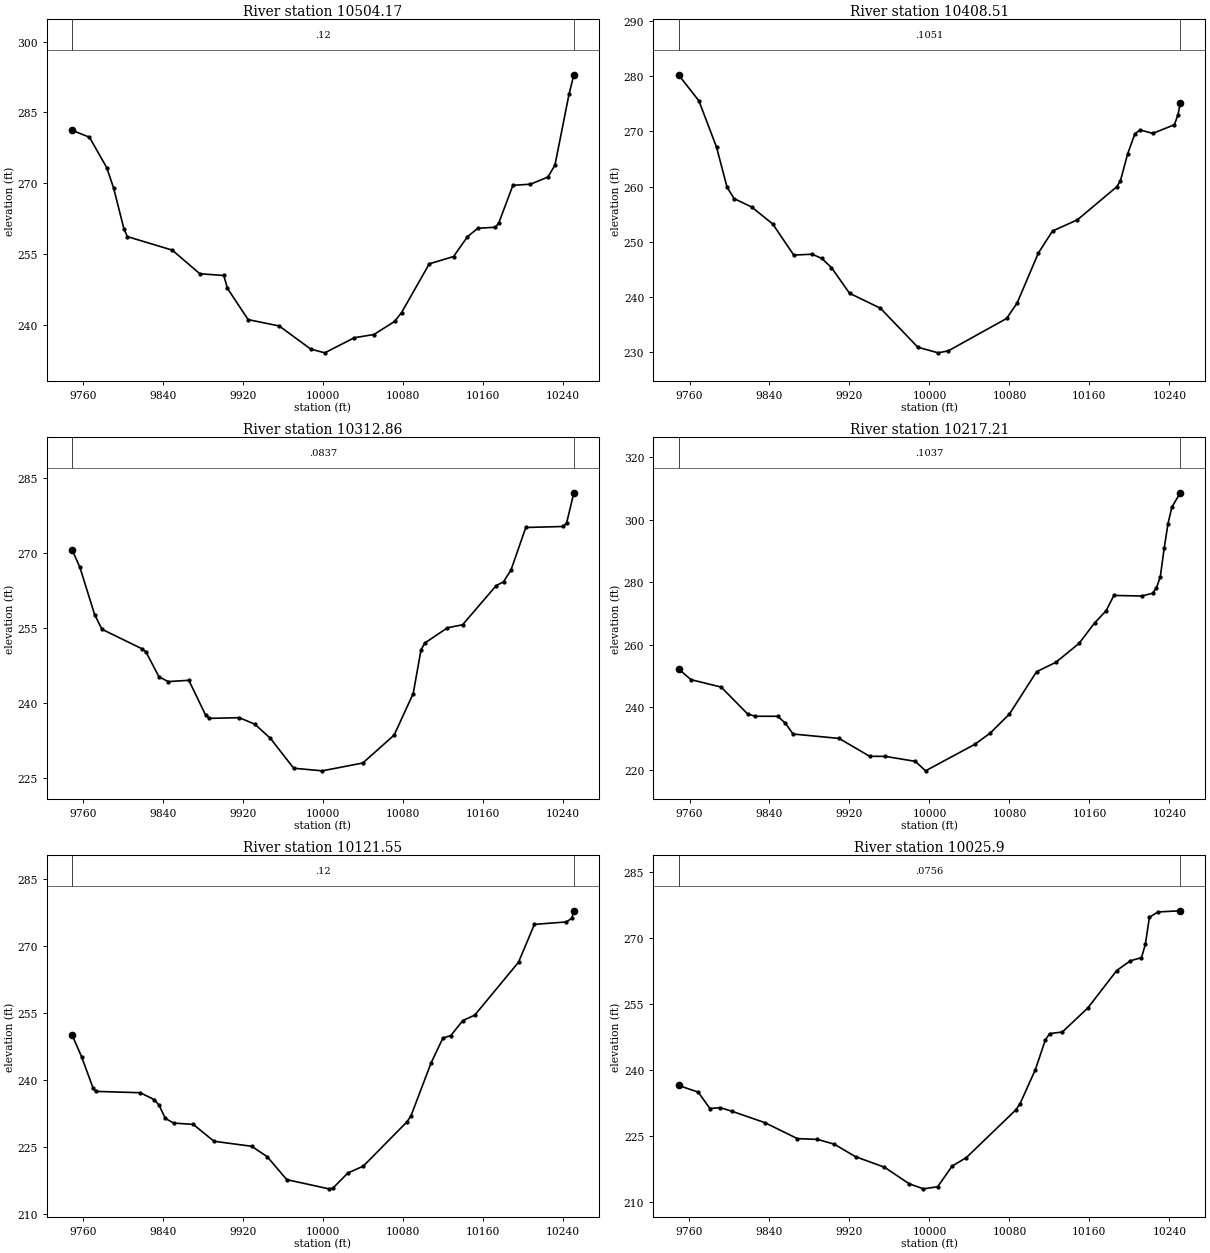
Type RM Length L Ch R = 1 ,10504.17,95.653400,95.653400,95.653400
XS GIS Cut Line= 6
 1188086.9752625844352.6846861631188019.84494411844146.859366236
1188007.73331452844115.6426744041187995.65246981844085.533697269
1187955.72361907843968.7225929131187921.64421663 843878.87197964
#Sta/Elev= 30
 9749.02281.21039766.409279.75059783.664273.30959790.566268.99819800.919260.3023
9804.369258.68319849.231255.82069876.839250.81179900.821250.44469904.446247.7108
9925.152241.0915 9956.21239.74589987.698234.851910001.81234.049710031.44237.2586
 10050.9237.9272 10071.7240.706910078.64242.588510106.37252.914510130.64254.4587
10144.51258.651610154.89260.446710172.46260.671110175.97261.6115   10190269.5575
10207.55269.788110225.09271.312310232.11273.870910246.15288.859310250.99 292.983
#Mann= 3 , 0 , 0
 9749.02    0.12       0 9749.02    0.12       010250.99    0.12       0
#XS Ineff= 2 , 0
       0                               0
Bank Sta=9749.02,10250.99
Exp/Cntr=0.3,0.1

Type RM Length L Ch R = 1 ,10408.51,95.653400,95.653400,95.653400
XS GIS Cut Line= 6
1188182.57323137844332.1958084361188122.26163445844171.797100173
1188089.95015934844055.0789434221188077.96857021 844018.55261612
1188049.83846771843949.1219016241188010.14173978843861.605991828
#Sta/Elev= 30
9749.011280.2915  9769.4275.55699786.994267.17499797.551259.88889804.589257.8261
9822.184256.29419843.297253.20939864.259247.57689882.646247.73319892.329246.9655
9902.011245.30279920.053240.64869950.962237.93329988.397230.855710008.75229.8387
10018.91230.203310077.19236.072610087.74238.889410108.97247.953810123.13251.9408
10147.91253.960210187.42259.976310191.02261.037410198.23265.908710205.43269.5645
10210.69270.281310223.44269.660510245.06271.227410248.66273.064210250.97275.1572
#Mann= 3 , 0 , 0
9749.011  0.1051       09749.011  0.1051       010250.97  0.1051       0
#XS Ineff= 2 , 0
       0                               0
Bank Sta=9749.011,10250.97
Exp/Cntr=0.3,0.1

Type RM Length L Ch R = 1 ,10312.86,95.653400,95.653400,95.653400
XS GIS Cut Line= 6
1188309.81260561844271.0097852411188233.42691384844125.148248728
1188204.24648301844078.6790270541188168.24717071844030.568803489
1188140.20922665 843987.625199591188057.94016339843837.718408247
#Sta/Elev= 30
9749.031270.58749756.904267.03649771.589257.62319778.932254.68949819.315250.7659
9822.987250.15239835.965245.20189845.187 244.2469865.838244.50259882.603237.5578
9886.312236.90419916.367237.03749931.863235.7347 9947.36232.92569970.711 226.947
9999.274226.423410039.87227.989710071.22233.565810090.29241.866110098.02250.5162
 10101.8251.944410124.53254.981210139.67255.594610173.17263.3873 10180.6264.1831
10188.04266.509510202.92275.020110240.51275.220910243.83276.001710250.98 281.951
#Mann= 3 , 0 , 0
9749.031  0.0837       09749.031  0.0837       010250.98  0.0837       0
#XS Ineff= 2 , 0
       0                               0
Bank Sta=9749.031,10250.98
Exp/Cntr=0.3,0.1

Type RM Length L Ch R = 1 ,10217.21,95.653500,95.653500,95.653500
XS GIS Cut Line= 6
1188383.92582598844209.2124119921188335.36354152844123.559818216
1188267.80270653844011.6348055521188257.66523457843991.245967945
1188238.74649001843955.6700118091188127.73446258843777.806429553
#Sta/Elev= 30
9749.025252.18339761.382248.77389791.675246.38029818.076237.80359825.618237.0464
 9848.26237.03779855.924234.81469863.588231.35839909.575229.95379940.233 224.226
9955.768224.2069  9985.9222.61459996.079 219.57510045.27228.041310060.74231.6385
10080.08237.791710107.15251.303310126.49254.318910149.69260.370510165.16266.8922
10176.76270.8418 10184.5275.716110212.36275.533510223.17276.416910227.04278.0818
10230.91281.685610234.78290.768310238.64298.744610242.51303.998410250.96308.5808
#Mann= 3 , 0 , 0
9749.025  0.1037       09749.025  0.1037       010250.96  0.1037       0
#XS Ineff= 2 , 0
       0                               0
Bank Sta=9749.025,10250.96
Exp/Cntr=0.3,0.1

Type RM Length L Ch R = 1 ,10121.55,95.653400,95.653400,95.653400
XS GIS Cut Line= 6
1188475.47889933844163.8260068121188430.55750533844089.629624746
1188352.73607997843968.0489984781188342.38508439 843949.89114674
1188323.45229782843918.3024400421188202.77847667843742.603076141
#Sta/Elev= 30
9749.009250.1092  9758.5245.21019770.006238.21559772.847237.4582 9817.19237.1599
9831.371 235.5969836.176 234.3189842.262231.41779850.779230.37359870.256230.0798
9890.948226.30939928.686225.18159944.268222.85429963.745217.731310005.85215.6699
10009.67215.765110024.97219.225910040.37220.745610084.15230.677810088.13232.0371
10108.03243.758410119.97249.380410127.93 249.95210139.87253.283610151.82254.5049
 10195.6266.335510211.52 274.80410243.36275.339710248.91276.155710250.98277.8398
#Mann= 3 , 0 , 0
9749.009    0.12       09749.009    0.12       010250.98    0.12       0
#XS Ineff= 2 , 0
       0                               0
Bank Sta=9749.009,10250.98
Exp/Cntr=0.3,0.1

Type RM Length L Ch R = 1 , 10025.9,95.653400,95.653400,95.653400
XS GIS Cut Line= 6
1188571.04059818844090.225535758 1188526.9740392844021.854378399
1188478.25911999843956.198420346 1188445.2850322843918.590464721
1188356.47468277843829.7318613671188256.23747326843701.108072961
#Sta/Elev= 30
9749.054236.49319768.732234.98689780.441231.27169790.782 231.4599802.894230.6162
9835.306228.07199867.988224.43959887.982224.26969904.756223.19029926.069220.3473
9955.001217.96319979.769214.20179993.938213.056810008.27213.531310022.62218.2011
10036.97220.148610086.26230.914110090.58232.326110105.97240.085710115.99246.8397
10120.23248.248310132.93248.615810158.34254.036510187.37262.559610201.11264.7711
10212.11265.480810215.98268.502110220.06274.631910228.62275.834210250.97276.1014
#Mann= 3 , 0 , 0
9749.054  0.0756       09749.054  0.0756       010250.97  0.0756       0
#XS Ineff= 2 , 0
       0                               0
Bank Sta=9749.054,10250.97
Exp/Cntr=0.3,0.1

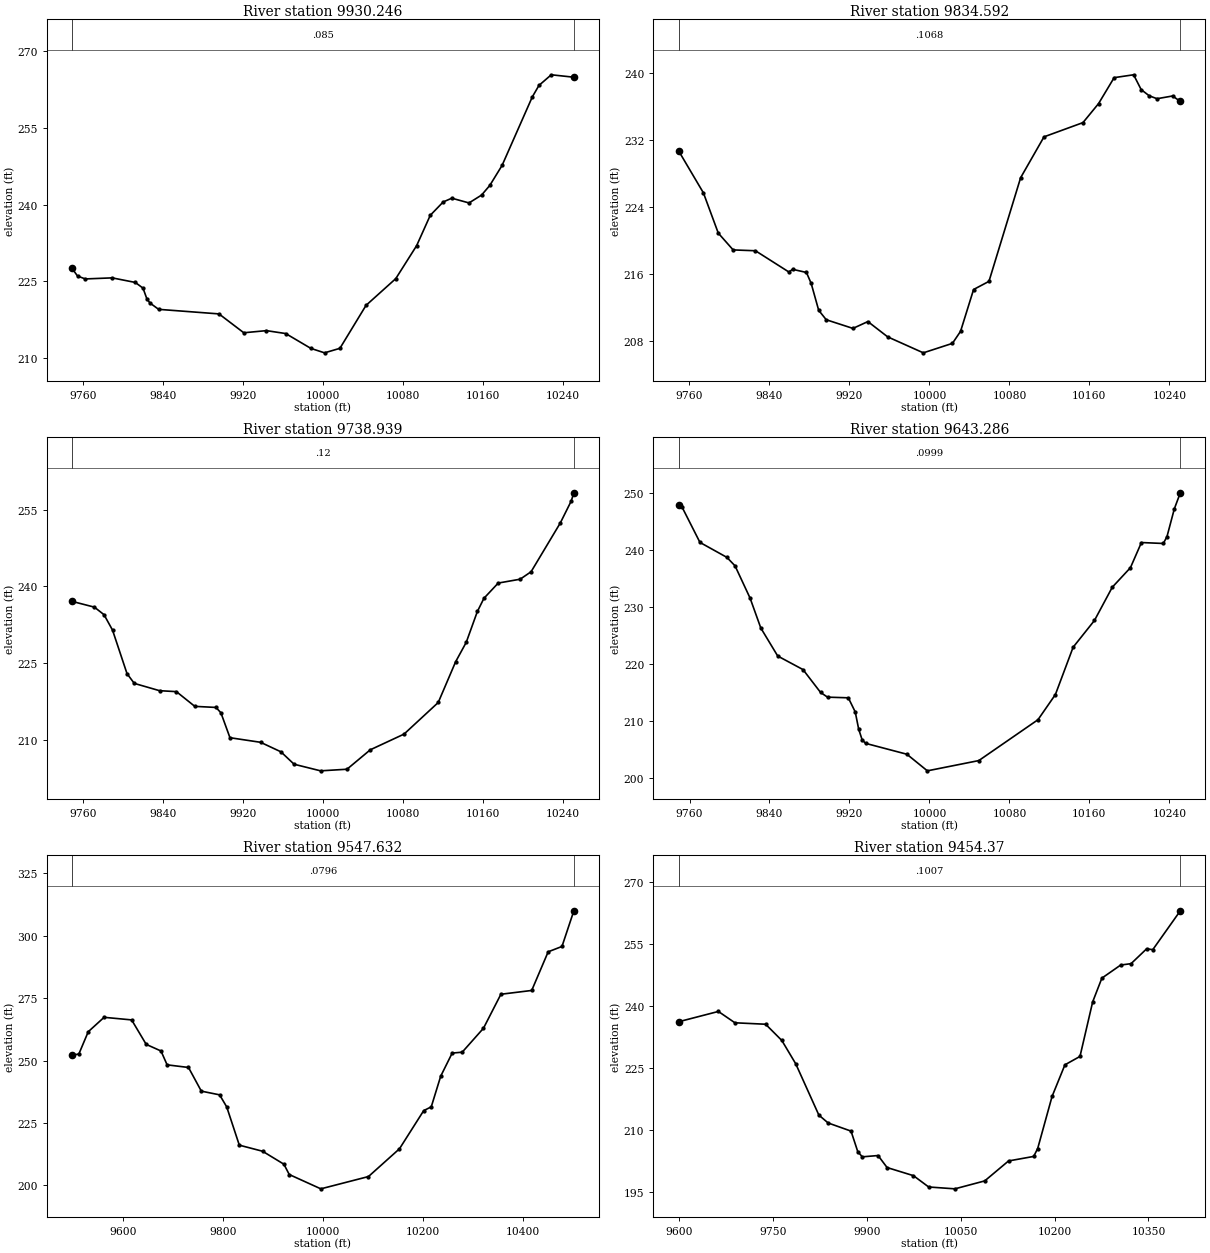
Type RM Length L Ch R = 1 ,9930.246,95.653400,95.653400,95.653400
XS GIS Cut Line= 6
1188631.97248541844032.4124388441188589.45660183843963.382213948
1188553.02345044 843911.014689281188474.89031245843812.170678561
1188389.67186234843712.0605609211188329.91077984843632.383617604
#Sta/Elev= 30
9749.035227.48779754.506226.00289762.212225.43189789.185225.64149812.304224.7438
 9820.01223.62459823.863221.52939827.002220.71169835.621219.47799896.004218.5848
9920.802214.88979943.448215.30769962.717214.73889987.866 211.83410001.58210.9596
10016.96211.8427 10043.1220.260610072.85225.497810093.72231.955110107.32237.8875
10120.25 240.50410128.87241.2436 10146.1240.315210158.66241.857210166.86243.7357
10179.16247.659610209.38261.071610216.07263.331510228.38265.412210250.97264.9345
#Mann= 3 , 0 , 0
9749.035   0.085       09749.035   0.085       010250.97   0.085       0
#XS Ineff= 2 , 0
       0                               0
Bank Sta=9749.035,10250.97
Exp/Cntr=0.3,0.1

Type RM Length L Ch R = 1 ,9834.592,95.653400,95.653400,95.653400
XS GIS Cut Line= 6
1188677.48734083843974.2571681231188613.39997392843853.935070552
1188583.58848297843802.1829244641188550.91331243843756.828307296
1188509.26913412843699.7368846081188412.46856876 843548.80123995
#Sta/Elev= 30
9749.049230.70679773.932225.68169788.801220.8799 9803.67218.87749825.973218.7777
9859.428216.24369863.145216.5645 9877.01216.18729881.731214.88269889.236211.6793
9896.808210.54879923.507209.51689938.457210.33169958.239208.50819993.904206.6028
10023.02207.732710031.14209.165910044.18214.156610059.56215.126210091.23227.4855
10114.62232.362310153.59234.059110169.18236.324810184.77239.421510204.26239.7643
10211.82237.994910219.85237.259410227.65236.909610243.24237.235610250.98236.5837
#Mann= 3 , 0 , 0
9749.049  0.1068       09749.049  0.1068       010250.98  0.1068       0
#XS Ineff= 2 , 0
       0                               0
Bank Sta=9749.049,10250.98
Exp/Cntr=0.3,0.1

Type RM Length L Ch R = 1 ,9738.939,95.653400,95.653400,95.653400
XS GIS Cut Line= 6
1188722.77264824843969.2426025471188661.21148249843827.711110378
1188647.81497511843778.5591997991188624.11133544843638.727709467
1188598.31895813843569.6969721651188562.95055337843497.172717328
#Sta/Elev= 30
9749.096237.0532 9771.44235.92489781.064234.4487 9789.56231.43899804.056 222.926
9811.303221.02629836.548219.60099853.428219.4137 9871.84216.53539893.015 216.326
 9897.94 215.283    9907210.40889937.605209.51399957.912207.65739971.145205.2243
9997.612203.935410024.03204.249210047.34208.048210081.07211.113410115.28 217.294
10132.69225.258310143.29229.052210154.42235.081310160.97237.653210175.27240.6326
10197.18241.385910208.13 242.84410237.33252.369810248.28256.666410250.91258.2774
#Mann= 3 , 0 , 0
9749.096    0.12       09749.096    0.12       010250.91    0.12       0
#XS Ineff= 2 , 0
       0                               0
Bank Sta=9749.096,10250.91
Exp/Cntr=0.3,0.1

Type RM Length L Ch R = 1 ,9643.286,95.653400,95.653400,95.653400
XS GIS Cut Line= 6
1188823.76723013843952.230196917 1188768.1800332843818.402909293
1188724.38691654843677.5367405841188695.27737613843595.918340393
1188672.40041191843541.5107767511188644.22497852843484.300236609
#Sta/Elev= 30
 9749.02247.92549752.532247.53099770.445241.32899797.383238.70589805.551237.2174
9820.601231.5489 9831.33226.30299848.239221.38969873.534219.01179891.119214.9972
9898.088214.17289918.863214.05849925.787211.5746 9929.25208.53829932.712206.6733
9936.175206.06439977.446204.15549997.921201.242210049.37203.041710108.58210.2128
   10126214.630110143.75222.9395 10165.1 227.639 10182.9233.466410201.07236.8941
10212.04241.306910233.98241.142810237.64242.362610244.95247.207910250.97250.0396
#Mann= 3 , 0 , 0
 9749.02  0.0999       0 9749.02  0.0999       010250.97  0.0999       0
#XS Ineff= 2 , 0
       0                               0
Bank Sta=9749.02,10250.97
Exp/Cntr=0.3,0.1

Type RM Length L Ch R = 1 ,9547.632,93.262100,93.262100,93.262100
XS GIS Cut Line= 6
1189034.99547174 844128.314412531188905.56763974843880.455287453
1188800.70411864 843619.282846061188753.88209915843519.834120588
1188670.74645149843382.5148052341188570.27074045843245.291701157
#Sta/Elev= 30
9499.028252.03179512.659252.64779531.327261.52489562.975267.2986 9617.96266.2607
9647.071256.46119676.591253.81349688.801248.26799731.492247.21769757.112 237.738
9793.606236.25579807.814231.42629832.969216.10779879.407213.67539922.013208.4799
9932.664204.35379995.761198.621110090.84203.538910152.77 214.65910201.14229.9393
10216.22231.447710235.08243.716910258.01252.980610278.01 253.33310320.44262.9097
10355.28276.5342 10416.8278.054210449.65293.522310477.25295.672810500.96309.9556
#Mann= 3 , 0 , 0
9499.028  0.0796       09499.028  0.0796       010500.96  0.0796       0
#XS Ineff= 2 , 0
       0                               0
Bank Sta=9499.028,10500.96
Exp/Cntr=0.3,0.1

Type RM Length L Ch R = 1 , 9454.37,93.262000,93.262000,93.262000
XS GIS Cut Line= 6
1189087.91033683 844004.366437311188963.21933482843776.289253505
1188895.42316497843607.0324794851188870.74877011 843557.89148823
1188800.57463736843448.832457612 1188695.3621449843309.356716529
#Sta/Elev= 30
9599.047236.19699662.719238.69679689.137235.95429738.199235.60349764.116231.6755
 9786.32226.03639823.326 213.6149838.129211.71229874.704209.74449885.508204.7604
9892.711203.52019917.921 203.8349932.327200.92929974.417198.96529998.789196.2248
10040.68195.775910088.36197.695410126.39202.521610166.59203.618910172.99205.5319
10195.97218.1316 10216.5225.781610240.59227.816410260.87241.022410275.58246.7555
10305.61249.924810322.21250.259710347.12253.855410356.93253.648410400.94263.0551
#Mann= 3 , 0 , 0
9599.047  0.1007       09599.047  0.1007       010400.94  0.1007       0
#XS Ineff= 2 , 0
       0                               0
Bank Sta=9599.047,10400.94
Exp/Cntr=0.3,0.1

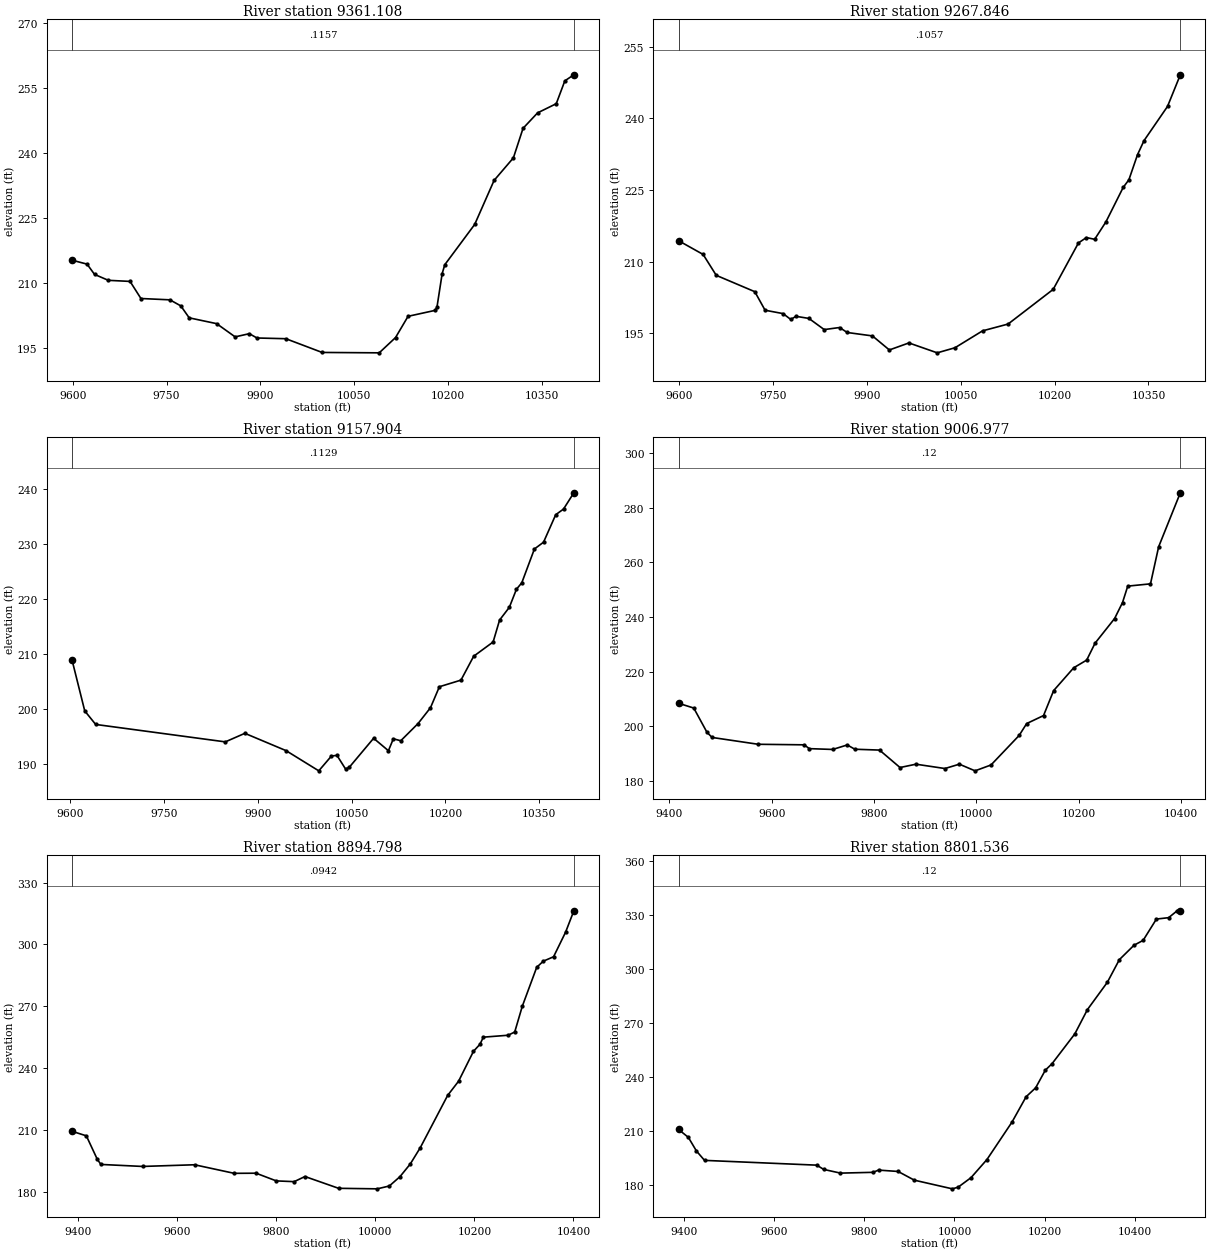
Type RM Length L Ch R = 1 ,9361.108,93.262100,93.262100,93.262100
XS GIS Cut Line= 6
1189227.55375521843919.557071535 1189042.5252945843653.826158709
1189013.85351475843622.0812929491188961.90492137843581.798792938
1188932.94394385843552.3316908561188726.24789929843297.435551419
#Sta/Elev= 30
9599.081215.27469623.052214.36519634.995211.99479656.983210.62459691.738210.3749
9709.115206.42579755.455206.11729772.833204.7218 9786.27201.95899830.061200.6197
9859.641197.56359882.337198.29969894.541197.30599940.709197.13759998.652193.9663
10089.89193.875410115.96197.4015   10136202.312310179.21203.683210182.11204.3633
 10190.5212.182310194.69214.230310242.47 223.53710273.46233.7051 10304.3238.9097
10319.72245.733310342.96249.303710372.79251.422710386.53256.704810400.93258.1031
#Mann= 3 , 0 , 0
9599.081  0.1157       09599.081  0.1157       010400.93  0.1157       0
#XS Ineff= 2 , 0
       0                               0
Bank Sta=9599.081,10400.93
Exp/Cntr=0.3,0.1

Type RM Length L Ch R = 1 ,9267.846,109.942200,109.942200,109.942200
XS GIS Cut Line= 6
1189277.44890716843865.9201295781189079.61893613843600.204491038
1189056.94317676843560.4535055011189037.11399909843502.126738891
1189014.01032336843467.0023995861188781.66649794843245.717351459
#Sta/Elev= 30
 9599.05214.36869638.336211.48929659.316207.11319720.926203.68739737.355199.8049
9766.106199.09969778.428197.86889786.643198.53199807.388198.09029831.823195.7523
9856.465196.18759868.564195.14439908.895194.42699935.933191.48649967.189 192.957
10012.45190.882910040.82191.948610084.84195.486510125.67196.911810197.76204.1764
10238.15213.901510250.78  215.0210264.03214.658610282.02 218.30510309.55225.5088
10318.73227.1282 10332.5232.378310342.88  235.3210380.42242.477610400.91249.1107
#Mann= 3 , 0 , 0
 9599.05  0.1057       0 9599.05  0.1057       010400.91  0.1057       0
#XS Ineff= 2 , 0
       0                               0
Bank Sta=9599.05,10400.91
Exp/Cntr=0.3,0.1

Type RM Length L Ch R = 1 ,9157.904,150.926800,150.926800,150.926800
XS GIS Cut Line= 6
1189416.29544716843777.2131229321189305.88403912843654.769824947
1189169.85264728843517.5722260511189122.90878359843460.086052779
1188962.40244636843346.9596271471188831.50863504843233.891509337
#Sta/Elev= 30
9603.395208.89069623.643199.65749641.117197.19329848.277194.02249879.516195.5778
9945.299192.43159997.645188.753210017.92191.451210026.72191.568410040.42 189.089
10046.16189.367810085.29194.676810108.94192.413610116.83194.586810128.65194.2247
10156.24197.346910176.19200.238810190.38204.052910224.87205.255810245.18209.5991
10276.26212.196510286.63216.191410302.17218.497910313.56221.797810322.06222.9539
10342.25229.115210356.83230.346610376.28235.345210388.76236.374910405.29239.3382
#Mann= 3 , 0 , 0
9603.395  0.1129       09603.395  0.1129       010405.29  0.1129       0
#XS Ineff= 2 , 0
       0                               0
Bank Sta=9603.395,10405.29
Exp/Cntr=0.3,0.1

Type RM Length L Ch R = 1 ,9006.977,112.179300,112.179300,112.179300
XS GIS Cut Line= 6
1189595.33218998843709.0415901691189374.00451317843465.022250965
 1189292.4231765843409.7077147221189172.87541175843359.058166668
1189019.80501679843272.5986851011188826.40619382843120.306479827
#Sta/Elev= 30
9417.802208.41399447.593206.65319473.321197.79929483.329195.8851  9573.6193.3806
9663.473193.17959673.537191.78279719.282191.48589747.761193.13849762.533191.5644
9810.834191.2549  9850.9184.86279882.037186.08129938.729184.49759966.937186.0884
9997.607183.648810028.82185.798210083.85196.622910098.53200.9703 10131.5203.8964
10151.25213.040310190.49221.404110215.91  224.2310232.29230.432910270.51239.4629
10285.93245.2941 10296.2251.331510340.66252.165810356.63265.7673   10399 285.533
#Mann= 3 , 0 , 0
9417.802    0.12       09417.802    0.12       0   10399    0.12       0
#XS Ineff= 2 , 0
       09869.987                       0
Bank Sta=9417.802,10399
Exp/Cntr=0.3,0.1

Type RM Length L Ch R = 1 ,8894.798,93.262100,93.262100,93.262100
XS GIS Cut Line= 6
 1189633.5266344843679.5277012881189447.86797145843447.906370729
1189385.08420321  843391.44721591189257.43737236843286.482218131
1189103.90010393843168.6210841241188899.87755314   842986.309974
#Sta/Elev= 30
9387.198209.32159416.044207.11899438.274195.66149445.477193.23079529.572192.2592
 9634.69193.0726 9714.77188.91389758.929188.97669799.748185.24389835.907184.8783
9857.728187.3662 9925.69181.643910003.73181.387210028.19182.772510049.69187.3017
10070.59193.4841 10090.7201.363910146.05226.759110168.09233.638710198.13 248.135
 10211.2251.543310218.16255.013510268.14255.944910281.48257.512110296.79270.0073
10325.94288.931210339.28291.901410359.99294.0423 10384.3305.987810400.98316.3632
#Mann= 3 , 0 , 0
9387.198  0.0942       09387.198  0.0942       010400.98  0.0942       0
#XS Ineff= 2 , 0
       09852.891                       0
Bank Sta=9387.198,10400.98
Exp/Cntr=0.3,0.1

Type RM Length L Ch R = 1 ,8801.536,193.432500,193.432500,193.432500
XS GIS Cut Line= 6
1189682.13774553843650.0138124081189347.66506711843300.398647547
1189310.08237341843251.2727877351189187.36353409843053.519715071
1189082.82516909842935.8525504321188956.13359964842812.877069101
#Sta/Elev= 30
9387.979 210.8779409.792206.44379427.729198.86049445.666193.65429694.692 190.995
9709.922188.62669747.188186.56719819.359187.00889831.533188.24819875.006187.4843
9910.977182.64219995.248177.821310008.14178.747710036.62184.023310071.95194.0942
10127.54214.931910158.89229.047910180.04234.014410201.54243.843310216.36247.4256
10266.97264.032410294.86277.523110339.08292.731910365.73305.321410398.16313.3264
10418.45316.052910447.88 327.89310475.01328.675810493.09332.342510500.93332.5068
#Mann= 3 , 0 , 0
9387.979    0.12       09387.979    0.12       010500.93    0.12       0
#XS Ineff= 2 , 0
       09859.869                       0
Bank Sta=9387.979,10500.93
Exp/Cntr=0.3,0.1

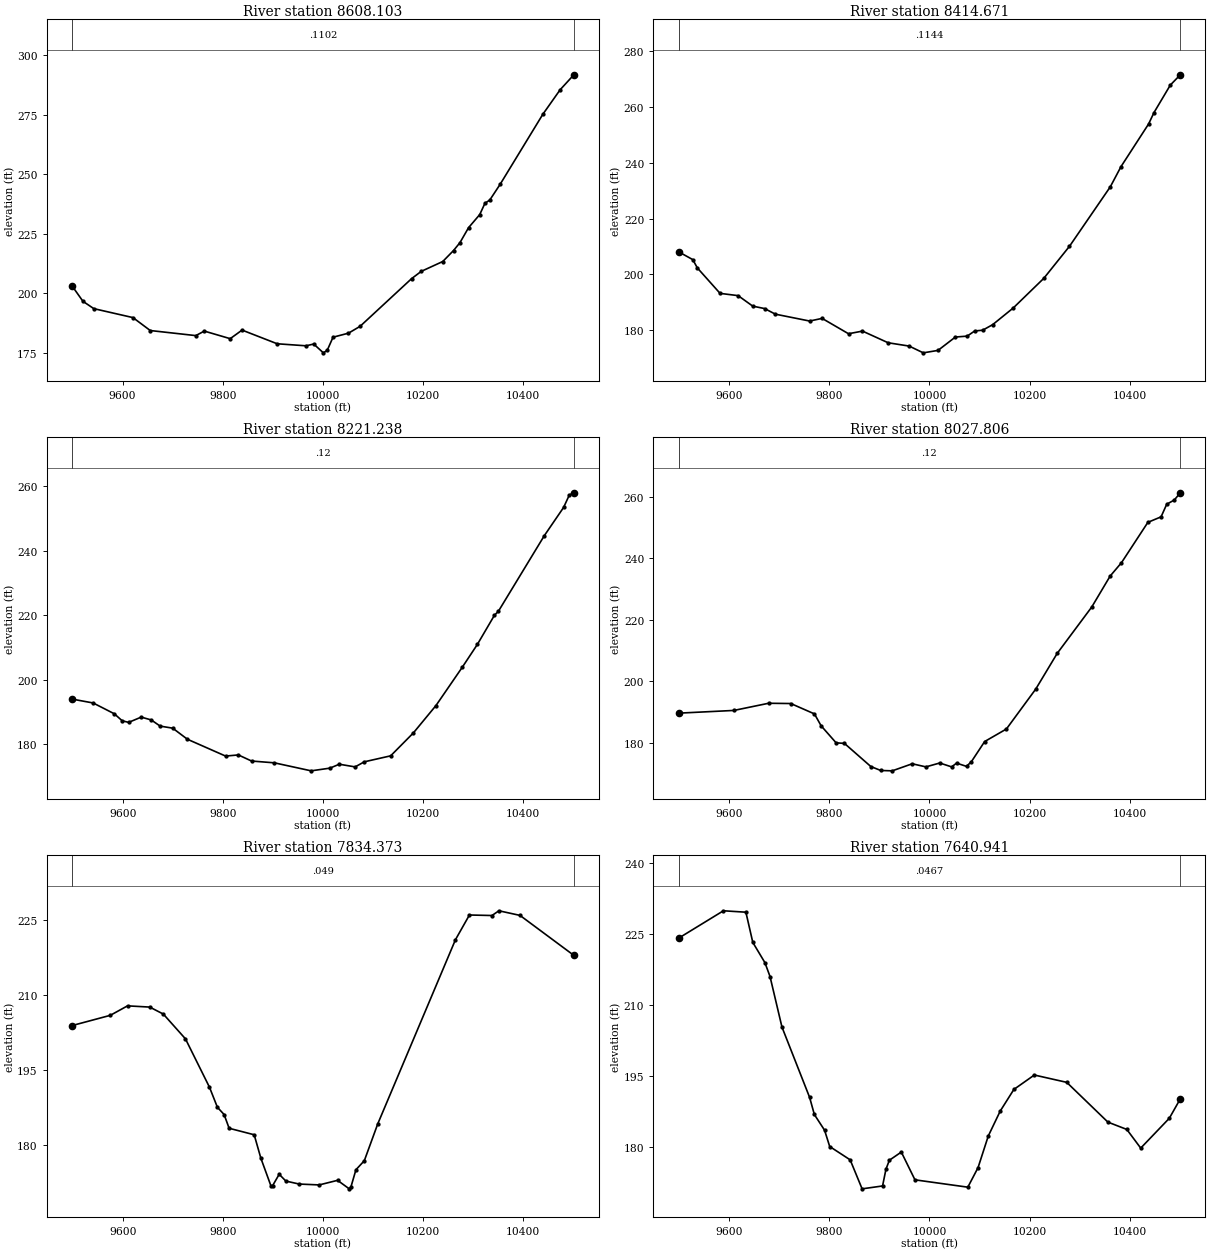
Type RM Length L Ch R = 1 ,8608.103,193.432400,193.432400,193.432400
XS GIS Cut Line= 6
1189733.08251444843493.0059760921189560.50077152843283.844777371
1189387.04312316843009.1520814551189312.99829028842904.768831255
1189222.84915172842803.4138267781189118.42691482842707.270631622
#Sta/Elev= 30
9499.059203.10539520.795196.63669542.494193.55259620.611189.79169655.194184.3505
9746.102182.21779763.091 184.1169814.795 180.9289838.499184.53669908.624178.7819
9966.199177.92949981.552178.673310000.79174.970810008.52176.0302 10020.1181.5445
10050.98183.244610074.15186.120910176.98 206.17310196.17209.220910239.22213.3761
10260.68217.988110273.55221.309210290.72227.609710312.99233.094410323.48237.8851
10333.03239.209710353.65245.798710438.98275.272810473.56285.595310500.95291.8901
#Mann= 3 , 0 , 0
9499.059  0.1102       09499.059  0.1102       010500.95  0.1102       0
#XS Ineff= 2 , 0
       0                               0
Bank Sta=9499.059,10500.95
Exp/Cntr=0.3,0.1

Type RM Length L Ch R = 1 ,8414.671,193.432500,193.432500,193.432500
XS GIS Cut Line= 6
1189919.49708163843411.7794586191189716.28005229843181.294835124
1189560.92363554842936.5390147921189506.82071528 842863.85783967
 1189405.1636617842762.5289273191189271.47926172842657.418747692
#Sta/Elev= 30
9499.049208.05459527.504205.23329536.609202.24749581.953193.10779618.057192.2892
9647.233188.51999670.852187.64879692.399185.63619760.761183.16719785.726184.1168
 9838.42178.60569866.323179.55229917.562175.36139959.604174.1684  9987.7171.7429
10017.12172.619710051.82177.421710075.35177.745110090.37179.599210106.14179.8679
10126.15 181.85610167.31187.855810228.31198.502310279.59 210.015 10361.2231.4056
10382.49238.643810437.59253.962710448.43258.083310480.98267.941810500.93271.6344
#Mann= 3 , 0 , 0
9499.049  0.1144       09499.049  0.1144       010500.93  0.1144       0
#XS Ineff= 2 , 0
       0                               0
Bank Sta=9499.049,10500.93
Exp/Cntr=0.3,0.1

Type RM Length L Ch R = 1 ,8221.238,193.432400,193.432400,193.432400
XS GIS Cut Line= 6
1190129.65682412843243.5821871161189824.04701121842994.498138309
1189776.72187506842942.767636171  1189735.459043842872.075254538
1189699.23859381842836.3823225891189351.09409894842630.912204431
#Sta/Elev= 30
9499.048194.04969541.158192.84579583.353189.50299599.176187.32629612.003186.8422
9637.144188.46769657.195187.59079674.855185.68629699.996185.04489729.327181.6146
9805.506176.41039831.099176.75439857.384 174.8739902.946174.31279976.373171.8336
10013.73172.664910032.61173.881510064.17173.052710082.49174.626110135.13176.4788
10180.49183.577410225.56192.045310278.14 203.91510308.19210.961210342.42 220.026
10350.14221.214110442.07  244.69 10480.4253.3854 10491.9257.2515 10500.9257.9301
#Mann= 3 , 0 , 0
9499.048    0.12       09499.048    0.12       0 10500.9    0.12       0
#XS Ineff= 2 , 0
       0                               0
Bank Sta=9499.048,10500.9
Exp/Cntr=0.3,0.1

Type RM Length L Ch R = 1 ,8027.806,193.432500,193.432500,193.432500
XS GIS Cut Line= 6
1190278.39452115842819.4540110371190105.41457608842754.833743284
1189950.69919299842722.0780676631189656.71764461842745.447670285
1189532.01222366842700.7004353061189331.89214681842592.969184127
#Sta/Elev= 30
9499.151 189.5689609.655190.4562 9678.94192.79269723.253 192.7069770.461189.3272
9783.822185.44139813.708179.90149830.311179.71929883.009172.18069902.726170.8964
9925.738170.77549965.632173.07739992.955172.0654 10020.6 173.32910044.26172.0669
10054.23 173.28510074.07172.225810083.91173.798310110.22180.320410153.68184.4102
10212.32197.440110254.98209.030310324.11224.1782 10360.8234.250310383.34238.5889
10436.06251.740910462.41253.536910473.71257.651410488.77259.010510500.83261.3739
#Mann= 3 , 0 , 0
9499.151    0.12       09499.151    0.12       010500.83    0.12       0
#XS Ineff= 2 , 0
       0                               0
Bank Sta=9499.151,10500.83
Exp/Cntr=0.3,0.1

Type RM Length L Ch R = 1 ,7834.373,193.432400,193.432400,193.432400
XS GIS Cut Line= 6
1190286.95396796842664.2215112061190061.40101106842595.168398619
1189735.66438756842535.6004698551189579.66080046842499.963197692
1189448.65512665842458.1340755361189321.69729393842406.416598327
#Sta/Elev= 30
9499.036 203.8369575.294205.8775 9609.79207.77479654.145207.52829681.301206.1293
9725.429201.18579773.392191.53059789.193 187.524 9802.59186.07589812.638183.3272
9862.681182.03169875.996 177.3539895.968171.86679899.297 171.8379912.612 174.142
9925.927172.78279952.557172.18889992.502172.015410029.16172.930210052.49171.2329
10055.82171.602510065.83175.045210082.59176.854410109.42184.211210264.59220.9898
10292.44225.917610337.44 225.81310351.33226.7599 10393.4225.838310500.97217.8565
#Mann= 3 , 0 , 0
9499.036   0.049       09499.036   0.049       010500.97   0.049       0
#XS Ineff= 2 , 0
       0                               0
Bank Sta=9499.036,10500.97
Exp/Cntr=0.3,0.1

Type RM Length L Ch R = 1 ,7640.941,193.432500,193.432500,193.432500
XS GIS Cut Line= 6
1190325.61076832842503.5003108541190261.01575861842479.470641469
1190162.18303839842447.1814847941189556.13261048842278.911628347
1189461.32798174 842249.491222821189366.23680576842215.996903662
#Sta/Elev= 30
9499.027224.06159588.641229.8642 9633.51229.56519647.316223.18299671.477218.9113
9681.697215.97749705.531205.29779760.761190.43689770.222186.82089790.651183.4921
9800.865180.05659841.723177.23899865.557171.11269906.414171.72049913.224175.2703
9920.033177.15889943.867178.88319971.106173.015610076.67 171.463 10097.1175.5982
10117.53182.281110141.36187.5444 10168.6192.114610209.46195.161410274.16193.6139
10356.37185.210810394.15183.6612 10421.9179.718410479.01186.026410500.98190.1336
#Mann= 3 , 0 , 0
9499.027  0.0467       09499.027  0.0467       010500.98  0.0467       0
#XS Ineff= 2 , 0
       0                10205.73       0
Bank Sta=9499.027,10500.98
Exp/Cntr=0.3,0.1