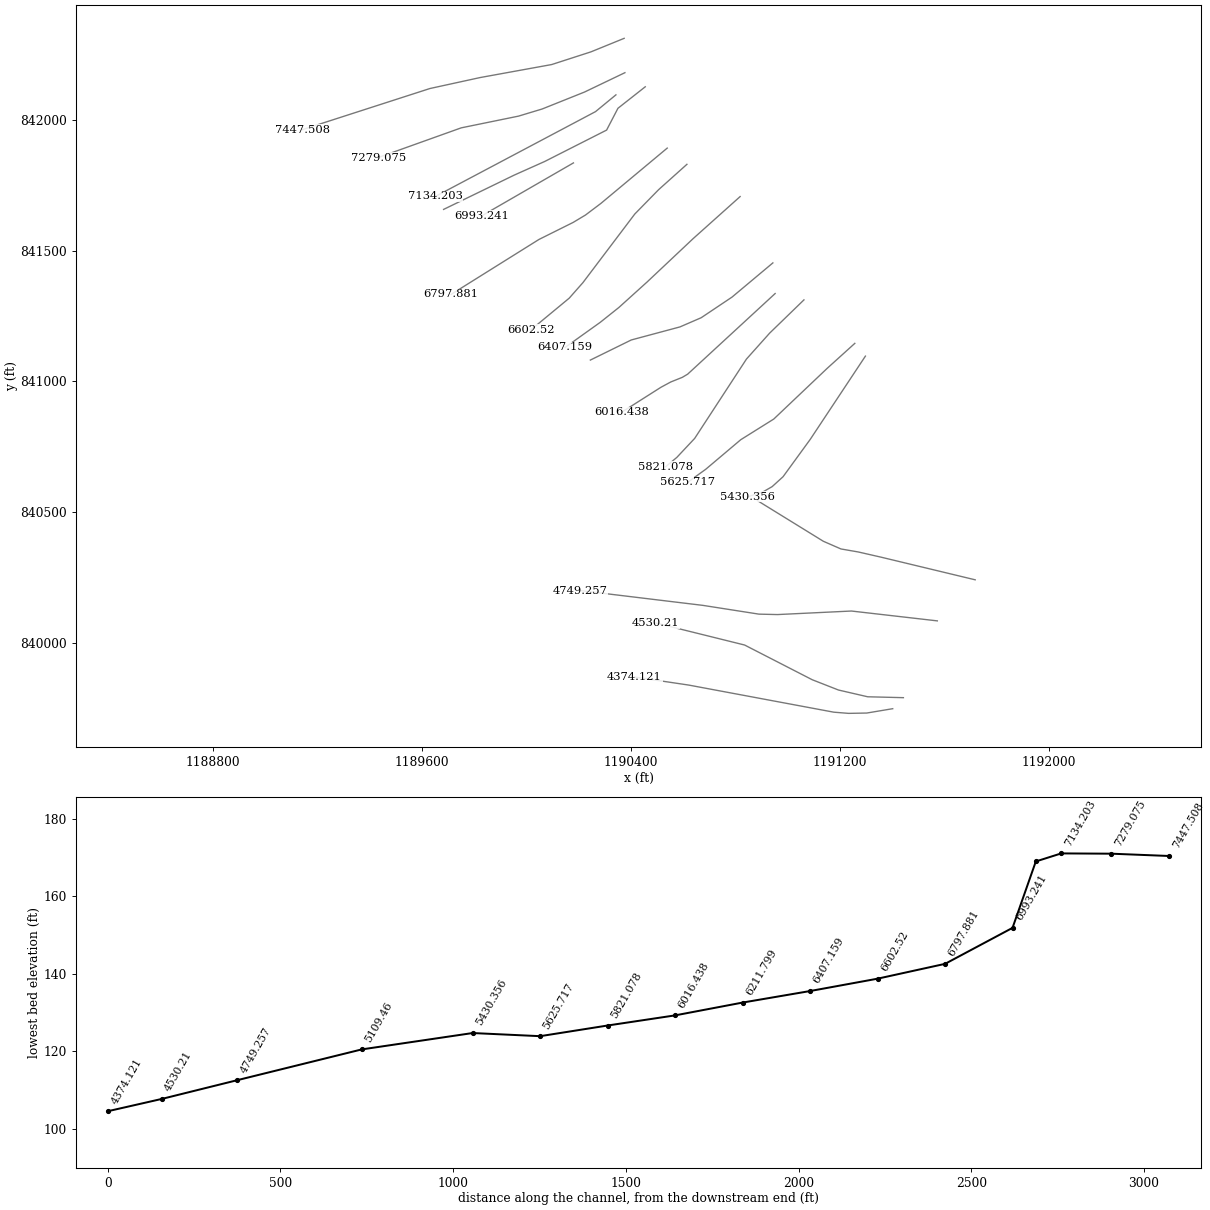
HEC-RAS study 103_ras.prj: 103

--- 103_ras.g01 (geometry) --- (continued)

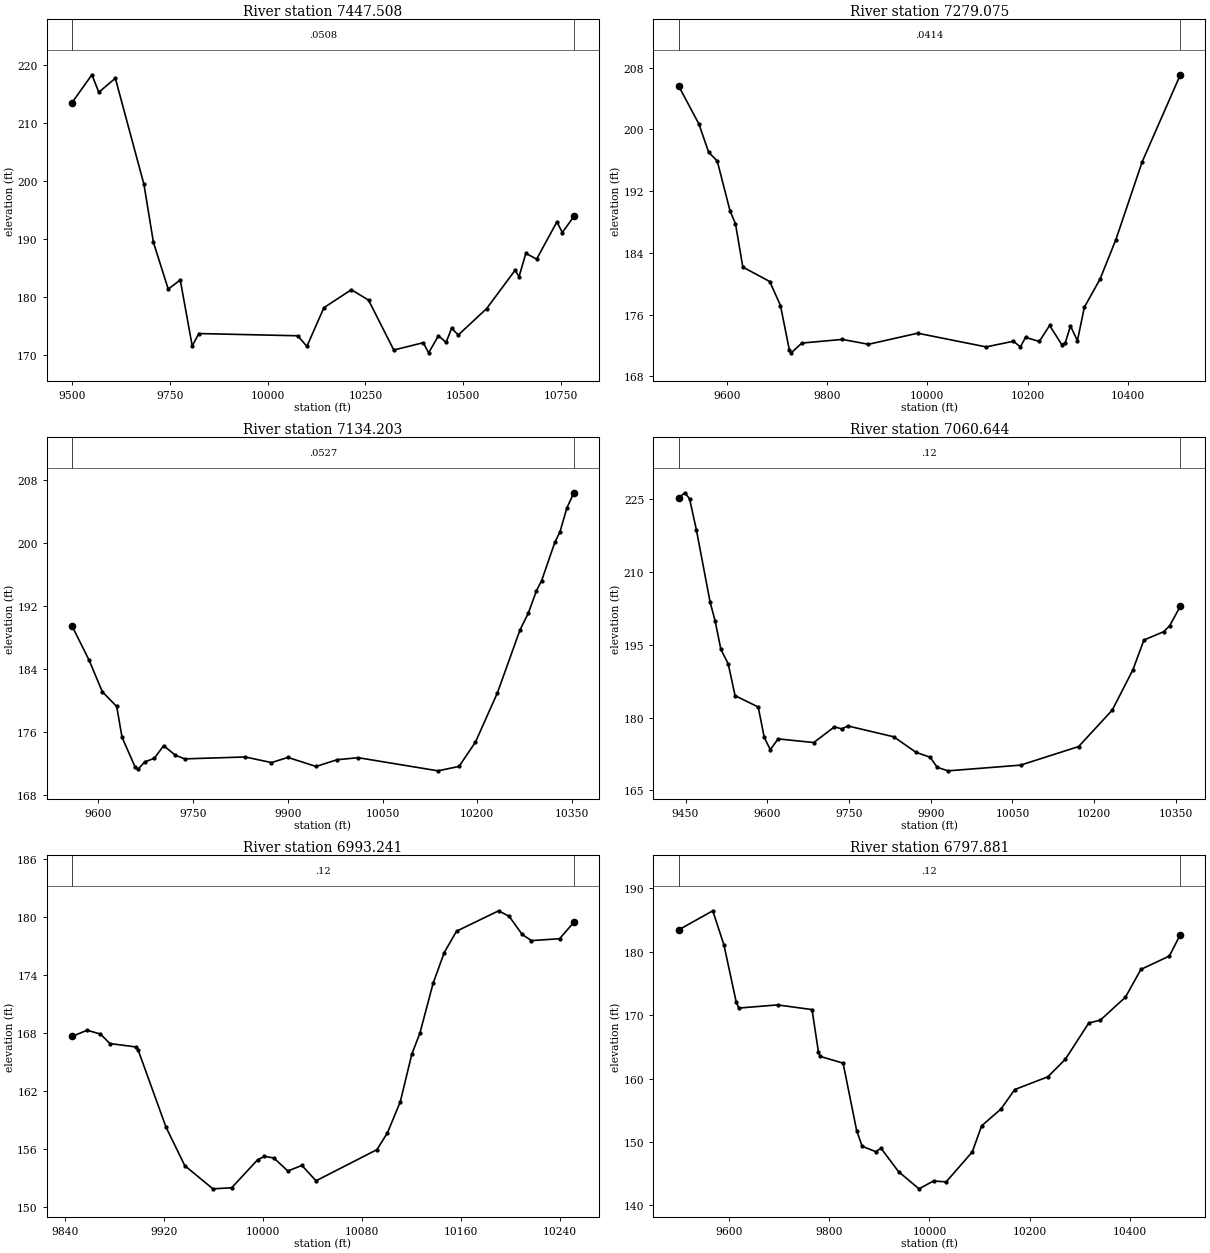
Type RM Length L Ch R = 1 ,7447.508,168.433800,168.433800,168.433800
XS GIS Cut Line= 6
1190373.32845148842312.4844695931190246.36956003842260.759861767
1190096.03423211842212.1570326831189822.17702186842162.401239872
1189630.07047024 842120.446970851189140.47107887841962.513812393
#Sta/Elev= 30
9499.029213.57439549.811218.36159567.556 215.3479609.829217.76559683.093199.4723
9707.383189.47849745.283181.43329776.073182.99799806.718171.62799823.628173.7729
10076.93173.389410100.36171.563610143.89178.2256 10214.3181.328710258.25179.5305
10322.92170.930510398.31172.195410412.07170.448610437.19173.381810456.95172.2505
10470.78174.678910488.08173.528610560.71178.079810633.35184.663910643.73183.6004
10661.03 187.592 10688.7   186.610740.58193.021410754.42191.182410783.98193.9459
#Mann= 3 , 0 , 0
9499.029  0.0508       09499.029  0.0508       010783.98  0.0508       0
#XS Ineff= 2 , 0
       09798.035        10174.02       0
Bank Sta=9499.029,10783.98
Exp/Cntr=0.3,0.1

Type RM Length L Ch R = 1 ,7279.075,144.871700,144.871700,144.871700
XS GIS Cut Line= 6
1190376.26791288842181.0123518181190221.67958697842106.930021512
1190059.57008907842042.0555680711189969.06563254842014.777751778
1189749.67170846841969.8519955191189432.42818344841856.366876215
#Sta/Elev= 30
9503.133205.6474 9543.82 200.6969563.354197.01689580.394195.90959605.995189.4311
 9616.85187.77429631.507182.15799685.289180.28419706.682177.1758 9724.51 171.382
9728.075171.04699749.468172.31459830.252 172.787 9882.34172.15489980.561173.5905
10117.44171.814810171.91172.554310185.66171.805610195.97173.049110223.46172.5203
10244.09174.597710268.37172.103210275.31 172.34710285.71174.527310299.59172.6191
10313.46176.964410344.89 180.614 10376.4185.721610428.93195.800110505.06 207.072
#Mann= 3 , 0 , 0
9503.133  0.0414       09503.133  0.0414       010505.06  0.0414       0
#XS Ineff= 2 , 0
       09806.928        10142.29       0
Bank Sta=9503.133,10505.06
Exp/Cntr=0.3,0.1

Type RM Length L Ch R = 1 ,7134.203,73.559400,73.559400,73.559400
XS GIS Cut Line= 3
1190341.85996777 842096.194367961190263.73496777842031.958256871
1189650.88774553841707.305479065
#Sta/Elev= 30
9558.267189.50579585.436185.13249606.099181.16769628.932179.28799637.427175.3775
9657.757171.66439662.471171.30499673.609172.2649 9688.46172.70759703.311174.3148
9721.875173.10019736.726172.63649832.382172.88019874.098172.16759900.087172.8224
 9944.64171.67439978.055172.530810011.47172.7876 10137.7171.118510171.12171.6793
10197.11174.771310231.87181.022610267.65189.006210280.93191.159410293.64193.9746
10301.96195.282210322.98200.172110330.77201.4099 10341.9204.501910352.94206.4215
#Mann= 3 , 0 , 0
9558.267  0.0527       09558.267  0.0527       010352.94  0.0527       0
#XS Ineff= 2 , 0
       09840.203        10114.71       0
Bank Sta=9558.267,10352.94
Exp/Cntr=0.3,0.1

Type RM Length L Ch R = 1 ,7060.644,67.402200,67.402200,67.402200
XS GIS Cut Line= 6
1190454.10281581842127.0332522551190349.57099531842044.742244602
1190306.20141018 841961.339196311190069.33675305  841841.2388068
1189952.57248542841788.972896517  1189682.346609841657.752100543
#Sta/Elev= 30
9437.192225.33689449.087226.37039457.438225.11799469.964218.72969495.017203.8935
9504.336199.94359514.944194.07299528.421191.07969540.948184.54089583.455182.1948
9594.549175.92059605.642173.39549619.919175.62389685.453174.8729  9723.4178.1166
9736.951177.67919747.987178.29089832.221176.05789873.055172.85349898.804171.8493
9912.024169.76399931.862169.038410065.02170.215710171.55174.048810233.29 181.573
10271.11189.8651 10291.4196.017910327.71197.728210338.61198.962210358.16202.9814
#Mann= 3 , 0 , 0
9437.192    0.12       09437.192    0.12       010358.16    0.12       0
#XS Ineff= 2 , 0
       09886.673        10121.86       0
Bank Sta=9437.192,10358.16
Exp/Cntr=0.3,0.1

Type RM Length L Ch R = 1 ,6993.241,195.360600,195.360600,195.360600
XS GIS Cut Line= 2
1190179.21709985841835.680130631 1189827.8184984841632.866740301
#Sta/Elev= 30
9845.759167.65359857.931168.28929868.728167.89559876.304166.9137 9897.31166.5648
9899.032166.29759921.761158.25399936.913154.28399959.641151.88829974.794151.9975
 9995.76154.886610001.31155.251110008.89 155.07710020.25153.735910031.61154.3089
10042.98 152.71710092.22155.938510100.77157.678910111.16160.899310120.46165.8183
10127.03167.994810137.68173.148910146.72176.329410156.62178.534510190.71180.6451
10199.22180.062210209.65178.204910217.23177.558910239.96177.756910251.49179.4534
#Mann= 3 , 0 , 0
9845.759    0.12       09845.759    0.12       010251.49    0.12       0
#XS Ineff= 2 , 0
       0                               0
Bank Sta=9845.759,10251.49
Exp/Cntr=0.3,0.1

Type RM Length L Ch R = 1 ,6797.881,195.360700,195.360700,195.360700
XS GIS Cut Line= 6
1190538.17743111841892.3481738911190284.19800695841680.572960962
1190225.34270878841636.2013183571190178.15795773841607.938398699
1190047.18191404841542.6734497011189711.41353227 841332.68572718
#Sta/Elev= 30
9499.075183.45429567.478  186.489589.761181.07239614.284172.07539619.473171.1249
9696.826171.62299765.583170.88299778.476164.17469781.916163.49469827.634162.4263
9854.727151.78069865.627149.31099892.876148.45859903.486148.98829938.374145.2983
9979.267 142.58910008.16143.830710033.41143.687710085.52148.410610104.24152.5306
 10143.1155.211710170.32158.2589 10236.6160.280710271.42163.046310318.09168.7545
10341.42169.227310391.47172.850910422.18177.2219 10479.1179.340810500.96182.7191
#Mann= 3 , 0 , 0
9499.075    0.12       09499.075    0.12       010500.96    0.12       0
#XS Ineff= 2 , 0
       0                               0
Bank Sta=9499.075,10500.96
Exp/Cntr=0.3,0.1

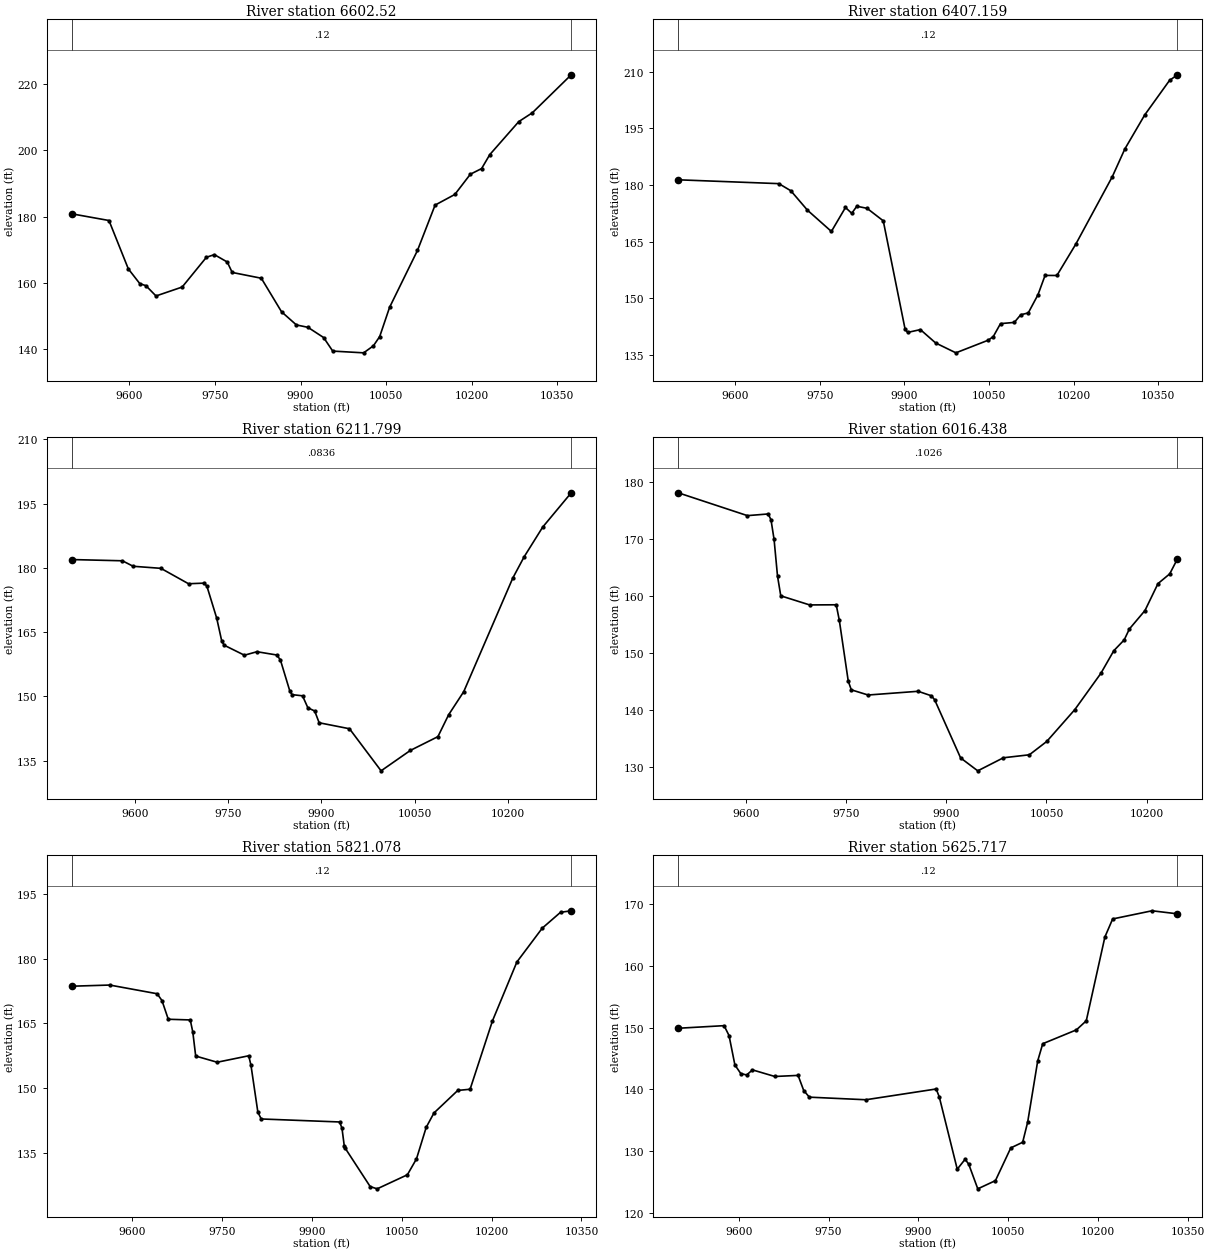
Type RM Length L Ch R = 1 , 6602.52,195.360600,195.360600,195.360600
XS GIS Cut Line= 6
1190613.55377805841830.2839598781190505.04723118841733.068171041
1190414.12190914 841640.151591921190215.31620054841377.202158318
1190163.01963731841317.9700855961190016.00244631841196.397978604
#Sta/Elev= 30
9499.082180.80839564.029178.79499597.973 164.1569618.112159.69349628.808159.0782
9646.497155.96419692.386158.66699734.943167.67759748.892  168.479771.447166.2398
9780.145163.07989831.182  161.339866.682151.17629892.707147.20299912.955146.4809
9940.512143.37799956.446139.287210010.68138.758810027.77140.883310038.81143.6847
 10056.2152.547510105.04169.727410135.95 183.45610170.57186.671510197.82192.7983
10217.54194.507610231.91198.733210282.75208.7175 10306.5211.379510374.75222.8835
#Mann= 3 , 0 , 0
9499.082    0.12       09499.082    0.12       010374.75    0.12       0
#XS Ineff= 2 , 0
       0                               0
Bank Sta=9499.082,10374.75
Exp/Cntr=0.3,0.1

Type RM Length L Ch R = 1 ,6407.159,195.360700,195.360700,195.360700
XS GIS Cut Line= 6
1190817.17253196  841706.83916311190637.74324347841546.249958598
1190460.44095451841379.2549969391190352.98295954841282.224134885
1190281.78011631841225.5126781821190147.76472084 841129.75078161
#Sta/Elev= 30
9499.014181.4016 9677.39180.38559698.666178.50079728.183173.34959770.561167.7194
9795.492174.06599806.617172.52839815.631174.39849833.773173.84549862.484170.5359
9901.263  141.77 9905.77140.97799928.304141.72089955.346138.17839991.209 135.568
10048.64138.925110057.49139.884710070.27143.303110094.72143.628410106.16 145.658
10119.43146.135910136.66150.944410149.25156.074610170.22156.057110203.77164.3716
10268.42182.227710290.61189.558410325.91198.590710369.84  207.7310383.92209.2199
#Mann= 3 , 0 , 0
9499.014    0.12       09499.014    0.12       010383.92    0.12       0
#XS Ineff= 2 , 0
       0                               0
Bank Sta=9499.014,10383.92
Exp/Cntr=0.3,0.1

Type RM Length L Ch R = 1 ,6211.799,195.360600,195.360600,195.360600
XS GIS Cut Line= 6
1190942.55038443841452.984635061 1190786.3084363841322.197680536
1190668.16058606841243.1333957041190586.93139146841207.976745889
1190400.59104807841158.0232344191190243.98480826841081.081318785
#Sta/Elev= 30
9499.085181.91329580.131181.62789597.441180.3456 9642.06 179.864 9686.43176.2677
9711.411176.40969715.929 175.7219731.707 168.2469739.825162.89079743.786 161.916
 9776.24159.58389796.451160.39829827.847159.64359833.958158.54429849.125151.2763
9852.767150.38129869.648150.10559878.266 147.3029889.194146.56319896.381143.8129
 9945.12142.41699995.918132.590410042.99137.358510087.22140.573710104.49145.6859
10128.72151.070710207.54177.582410225.86182.565910255.68 189.50110301.52197.5035
#Mann= 3 , 0 , 0
9499.085  0.0836       09499.085  0.0836       010301.52  0.0836       0
#XS Ineff= 2 , 0
       0                               0
Bank Sta=9499.085,10301.52
Exp/Cntr=0.3,0.1

Type RM Length L Ch R = 1 ,6016.438,195.360600,195.360600,195.360600
XS GIS Cut Line= 6
1190951.20352865841335.7115780561190616.40698368841027.152126887
1190595.99278608841015.003577399 1190551.6471988840997.181505218
1190514.02141787840976.872868627 1190364.3603438 840881.76870677
#Sta/Elev= 30
9499.081 178.1629602.659174.1443 9633.69174.43819637.944173.41899642.556169.9621
9647.701163.5141 9652.58 160.0479695.751158.44679735.516158.47249740.081155.8016
9753.541145.04579758.086143.52359783.247142.61089858.081143.26599878.058142.4683
9882.798141.77059921.618131.55479947.274129.28159985.637131.577710024.53132.1036
10050.54134.450310092.53140.0505 10131.4146.404710150.84150.402210166.38152.2985
10174.16154.222510197.48157.465910216.92 162.19510234.48163.905910246.09166.5509
#Mann= 3 , 0 , 0
9499.081  0.1026       09499.081  0.1026       010246.09  0.1026       0
#XS Ineff= 2 , 0
       0                               0
Bank Sta=9499.081,10246.09
Exp/Cntr=0.3,0.1

Type RM Length L Ch R = 1 ,5821.078,195.360700,195.360700,195.360700
XS GIS Cut Line= 6
1191061.48942811841311.4622316461190930.31306833841184.346282108
1190841.40874589841084.8843792011190643.27340298840781.310376943
1190575.02409162840708.6264470421190532.66888826840673.184297737
#Sta/Elev= 30
9499.045 173.606 9562.18173.87499641.304171.86179649.374170.29169659.945165.9496
9696.666165.79269700.926 162.959 9705.73 157.427 9741.58155.99239794.308157.4906
9798.045155.29139809.571144.42079815.214  142.859946.192142.15549950.066140.6882
9953.941136.5463 9955.23136.12639997.168127.1888 10008.8126.664810059.27129.9203
10074.49  133.6110090.74140.918710103.68144.241410143.44149.460910164.02149.7352
10201.44165.594210242.21179.223910284.52187.048910315.03190.722210332.97191.0797
#Mann= 3 , 0 , 0
9499.045    0.12       09499.045    0.12       010332.97    0.12       0
#XS Ineff= 2 , 0
       0                10315.61       0
Bank Sta=9499.045,10332.97
Exp/Cntr=0.3,0.1

Type RM Length L Ch R = 1 ,5625.717,195.360600,195.360600,195.360600
XS GIS Cut Line= 6
1191256.18493059841145.0440581491191150.24874988841049.266587776
1190946.01518055840855.3790459581190819.64448638840776.303422883
1190685.26858084840662.8828356291190617.54740316840613.957124403
#Sta/Elev= 30
9499.079149.88539575.701 150.3059583.947148.70149593.731143.94569603.515142.5581
9613.299142.32979623.083143.15199660.339142.08439699.151142.25989708.572139.8103
9717.993138.73869812.206138.31989929.577 140.0629934.742138.78169964.717 127.087
9977.805128.68839983.846127.9057    9999123.909210028.46125.238310054.05130.5311
10073.89131.442910082.25134.709310099.01 144.61610107.37147.383510163.55149.6238
10180.01151.088410211.08164.647710224.05167.5674 10289.8168.8886 10332.2 168.394
#Mann= 3 , 0 , 0
9499.079    0.12       09499.079    0.12       0 10332.2    0.12       0
#XS Ineff= 2 , 0
       0                10304.29       0
Bank Sta=9499.079,10332.2
Exp/Cntr=0.3,0.1

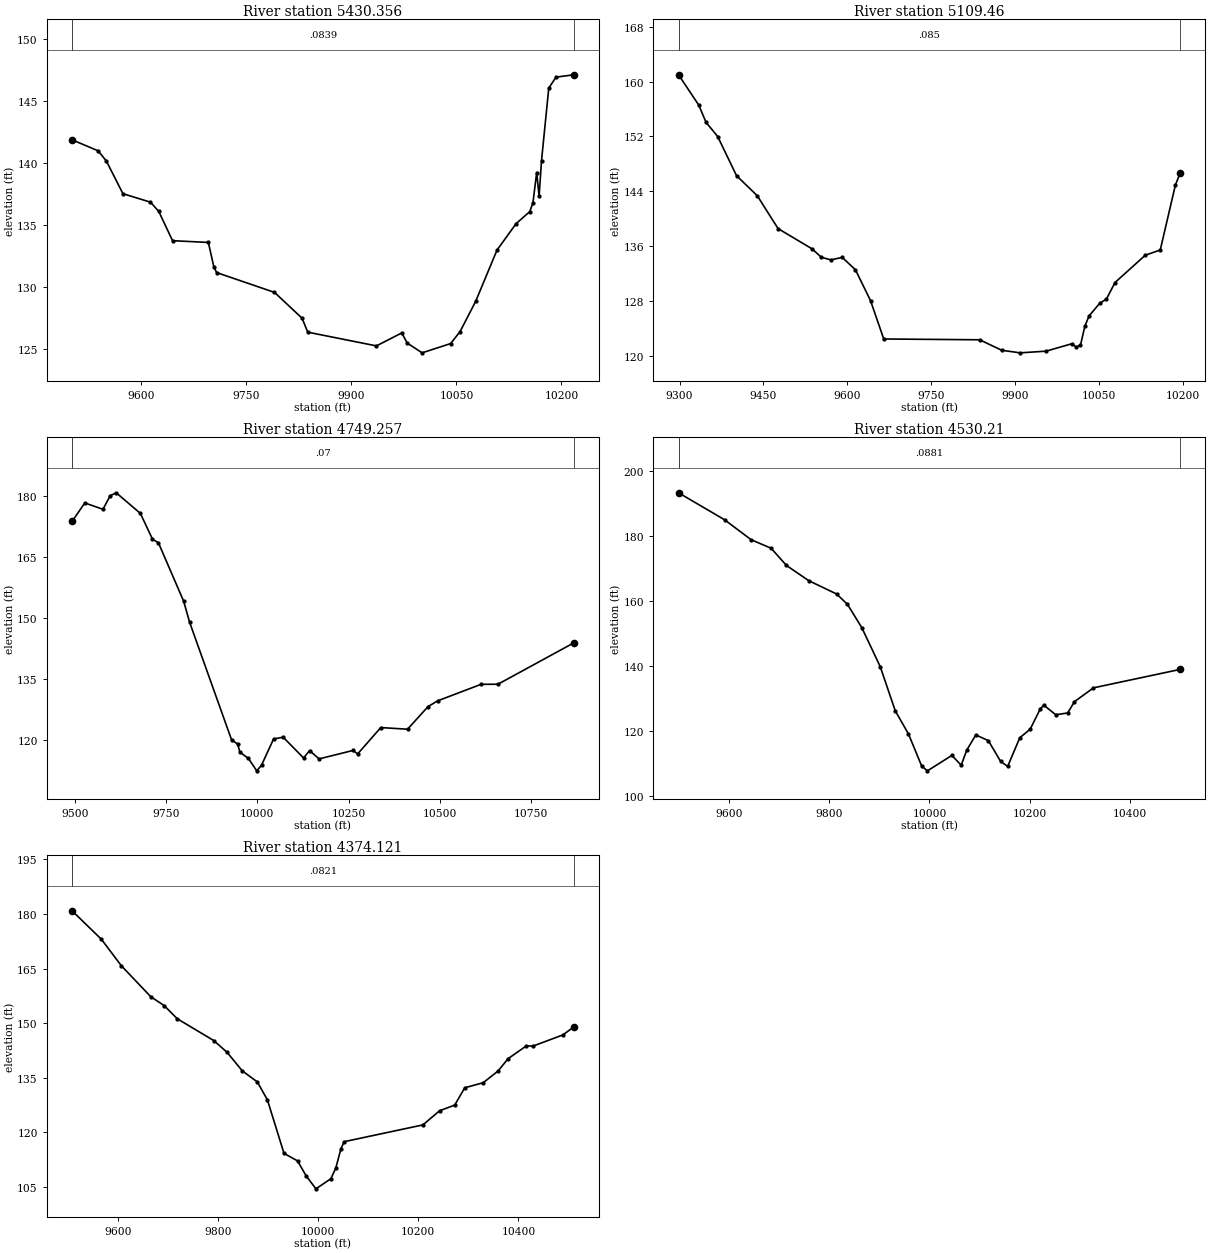
Type RM Length L Ch R = 1 ,5430.356,320.896500,320.896500,320.896500
XS GIS Cut Line= 6
1191296.72107884 841096.194367961191085.55025047840777.521440908
1190981.50718832840634.5823862111190939.96989214840596.855635703
1190906.84622383 840577.738590361190847.06830108840557.999923512
#Sta/Elev= 30
9501.033141.90429538.261141.01479550.068140.18639573.683137.55759613.041136.8726
9624.848136.13219644.527 133.7669695.693133.62559703.564131.6513  9707.5 131.195
9790.152 129.5979829.509127.51719837.675126.38749935.762 125.2819971.925126.3247
9979.749125.5092   10001124.720310041.77125.467710055.23126.434910077.45128.8641
10107.97133.004210135.29135.143310154.82136.112610159.35136.828610164.65139.2651
 10168.1 137.34510171.56140.216910181.92146.071110192.29146.958910217.77 147.149
#Mann= 3 , 0 , 0
9501.033  0.0839       09501.033  0.0839       010217.77  0.0839       0
#XS Ineff= 2 , 0
       0 9875.94                       0
Bank Sta=9501.033,10217.77
Exp/Cntr=0.3,0.1

Type RM Length L Ch R = 1 , 5109.46,360.203000,360.203000,360.203000
XS GIS Cut Line= 6
1191716.87130699840240.0362592791191357.87419158840326.394177392
1191269.90757143840346.5031032561191203.11782545840358.139293298
1191135.79183602840387.5071855931190883.37319774840543.204663406
#Sta/Elev= 30
9298.207160.98459334.453156.56129347.286154.07369368.198151.99659401.942146.2886
 9439.06143.36559476.179138.58659536.919135.63929553.791134.39959570.663134.0304
9590.909134.3941 9614.53132.59269641.526128.09459665.147122.51079836.748122.3937
9876.121120.8679 9909.06120.49329955.317120.736310001.57121.819710009.28121.3454
10016.99121.6007 10024.7124.354510032.41125.888610051.69127.737410063.25128.3044
10078.67130.729410132.64134.699110159.62135.4758 10186.6144.9056 10195.5146.7453
#Mann= 3 , 0 , 0
9298.207   0.085       09298.207   0.085       0 10195.5   0.085       0
#XS Ineff= 2 , 0
       0                               0
Bank Sta=9298.207,10195.5
Exp/Cntr=0.3,0.1

Type RM Length L Ch R = 1 ,4749.257,219.047100,219.047100,219.047100
XS GIS Cut Line= 6
1191571.97832714840082.8554786211191243.22711112840120.559755406
1190960.12477686840107.0028018721190889.29791568840108.649536363
1190674.85826175840142.1696281351190205.36853297 840198.90513008
#Sta/Elev= 30
9492.046173.74379527.046178.26759576.679176.71019596.532180.03519613.076180.7615
9679.286175.7052 9712.34169.41189728.836168.48069797.949154.15819814.404148.9475
 9929.29120.14289945.723119.14819952.296117.08659975.302 115.6139998.313112.5493
10011.47113.954410044.37120.366610070.68120.800210126.56115.714110142.97117.5047
10169.22115.483710261.69117.539710274.97116.709610338.28123.163510411.57122.7615
10467.75128.300510494.19 129.72810613.16133.770810659.43133.797210867.51143.9532
#Mann= 3 , 0 , 0
9492.046    0.07       09492.046    0.07       010867.51    0.07       0
#XS Ineff= 2 , 0
       0                               0
Bank Sta=9492.046,10867.51
Exp/Cntr=0.3,0.1

Type RM Length L Ch R = 1 , 4530.21,156.088400,156.088400,156.088400
XS GIS Cut Line= 6
 1191442.1022358 839788.95869829 1191305.3840102839792.361545987
1191193.43457878839818.2859106251191093.00611648839857.657266442
1190834.38460602839990.4403864711190494.20132686840074.814536473
#Sta/Elev= 30
9499.061193.15539591.043184.85619643.926178.73759684.024176.09769714.387 170.842
9758.841166.1593 9814.67162.0466 9836.15158.90979864.952151.71159901.778139.7199
9931.729126.16579958.168119.03049984.608109.13649995.939107.695110044.82112.4297
10063.47 109.41910074.36114.003610092.52118.731210117.56116.990610142.27110.5769
10156.26109.053810180.41117.873610201.12120.477810221.66126.833810228.46127.8714
10252.23124.9312   10276125.479410289.59128.957710327.57133.204610500.95138.8822
#Mann= 3 , 0 , 0
9499.061  0.0881       09499.061  0.0881       010500.95  0.0881       0
#XS Ineff= 2 , 0
       0                               0
Bank Sta=9499.061,10500.95
Exp/Cntr=0.3,0.1

Type RM Length L Ch R = 1 ,4374.121,0.000000,0.000000,0.000000
XS GIS Cut Line= 6
1191401.26312525 839746.756235941191301.95381457 839730.12493153
1191232.71630949839728.8342226881191175.65660984839733.413804733
1190620.39410776839837.1733710461190413.14326308839868.065393221
#Sta/Elev= 30
9508.911 180.8919567.662173.03519607.307165.78319666.386157.24989692.679154.8649
 9719.01151.22689791.906145.24189818.587141.98789848.712136.92959878.838133.8822
9898.922128.9512 9932.04114.26849959.174112.1913 9975.87108.1748 9995.75104.5215
10025.58107.291910035.53110.246310045.48115.420310052.12117.473610209.33122.0785
10242.78125.970710272.89127.525110292.96132.281610329.59133.652310359.51136.8983
10379.46140.272810415.99143.787110429.23143.729610488.81146.793610510.77148.9993
#Mann= 3 , 0 , 0
9508.911  0.0821       09508.911  0.0821       010510.77  0.0821       0
#XS Ineff= 2 , 0
       0                               0
Bank Sta=9508.911,10510.77
Exp/Cntr=0.3,0.1